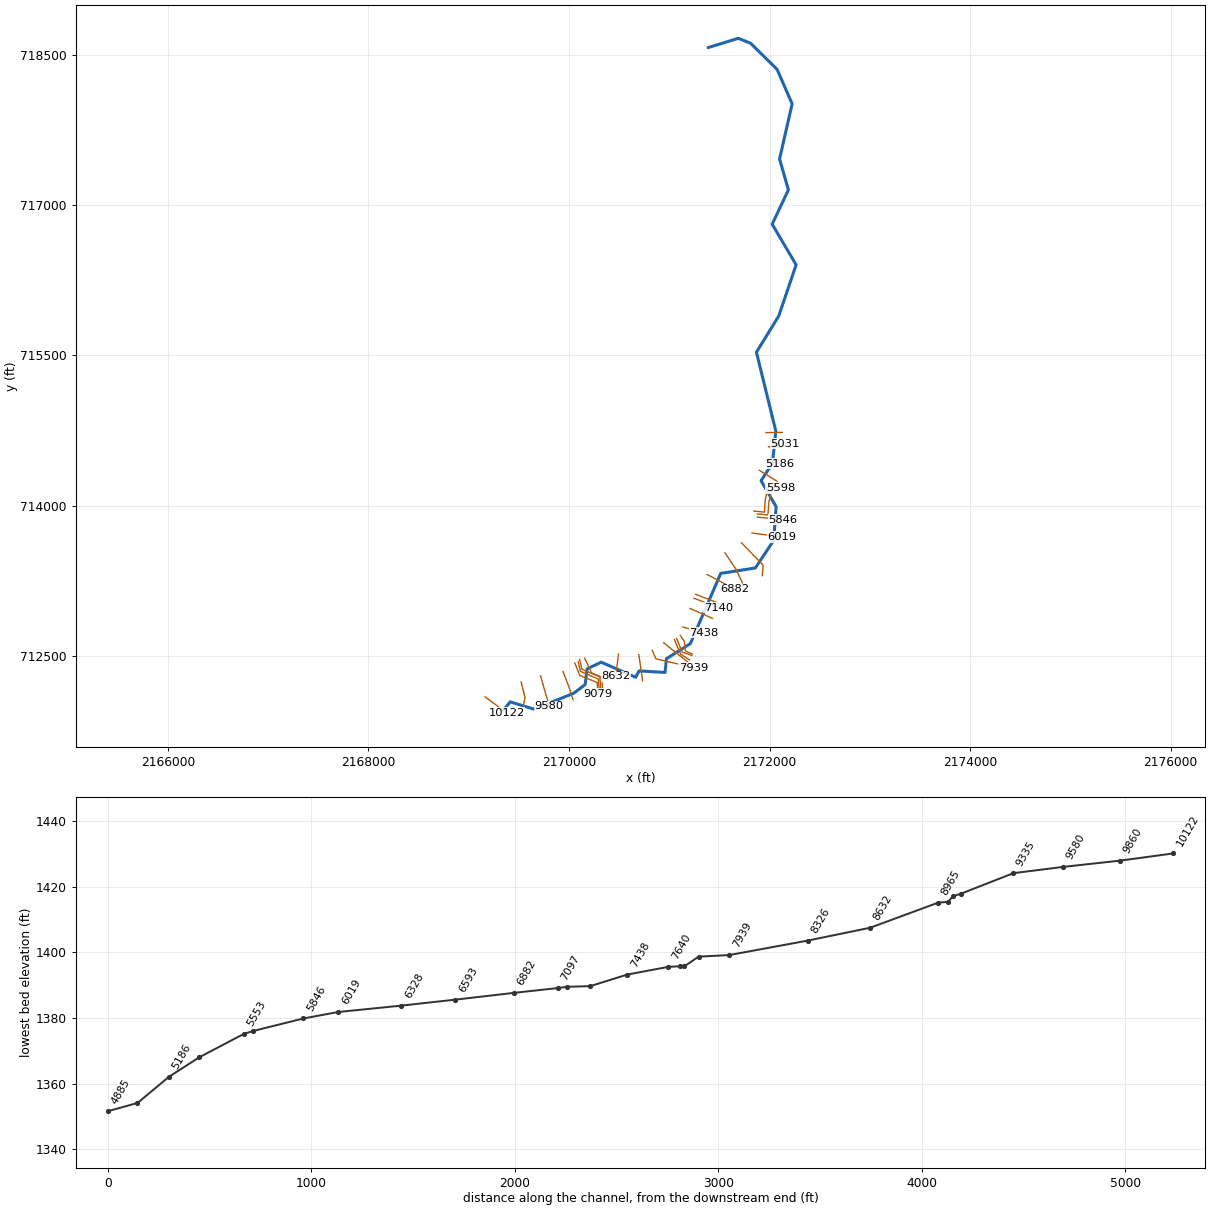
--- GLADYFK.prj (project) ---

Proj Title=GLADYFK
Current Plan=p01
Default Exp/Contr=0,0
English Units
Geom File=g01
Flow File=f01
Plan File=p01
BEGIN DESCRIPTION:
---------- MODELED AS PART OF WVEMD CTP PROGRAM, 2023----------
Stream Name: Glady Fork
Flood Zone:  AFH
Upshur County, WV
HEC-RAS Version: RAS 6.3
Vertical Datum: NAVD88
Projection: NAD 1983 StatePlane West Virginia S FIPS 4702 (US Feet)
Terrain: 1-meter LIDAR (FEMA Region III 3DEP collected 2016-2018)
Land Use: 2019 NLCD
Hydrologic Method:
WV 2010 Regional Regression Equations
Additional Model Notes:
None
END DESCRIPTION:
DSS Export Rating Curves= 0
DSS Export Rating Curve Sorted= 0
DSS Export Volume Flow Curves= 0
DXF OffsetX= 0
DXF OffsetY= 0
DXF ScaleX= 0
DXF ScaleY= 0

--- GLADYFK.p01 (plan) ---

Plan Title=Floodplain
Program Version=4.00
Geom File=g01
Flow File=f01
K Sum by GR=0
Std Step Tol=0.01
Critical Tol=0.01
Num of Std Step Trials=20
Max Error Tol=0.3
Flow Tol Ratio=0.001
Split Flow NTrial=30
Split Flow Tol=0.02
Split Flow Ratio=0.02
Log Output Level=0
Friction Slope Method=1
Unsteady Friction Slope Method=2
Unsteady Bridges Friction Slope Method=1
Global Log Level=0
CheckData=False
Run HTab=0
Run UNet=0
Run PostProcess=0
UNET Theta=0
UNET Theta Warmup=0
UNET ZTol=0
UNET ZSATol=0
UNET MxIter=0
UNET MaxInSteps=0
UNET DtIC=0
UNET DtMin=0
UNET MaxCRTS=0
UNET WFStab=0
UNET SFStab=0
UNET WFX=0
UNET SFX=0
UNET DSS MLevel=0
UNET DZMax Abort=0
UNET Convert EG Bridges=0
UNET Use Existing IB Tables=0
UNET Froude Limit=0
UNET Froude Power=0
Write IC File=0
Echo Input=False
Echo Output=False
Write Detailed=0

--- GLADYFK.f01 (steady flow) ---

Flow Title=Flows
Program Version=6.31
Number of Profiles= 1
Profile Names=01pct
River Rch & RM=GLADYFK,Main            ,10122
     977
River Rch & RM=GLADYFK,Main            ,5031
    1180
River Rch & RM=GLADYFK,Main            ,470
    1370
River Rch & RM=GLADYFK,Main            ,0
    2150
Boundary for River Rch & Prof#=GLADYFK,Main            , 1
Up Type= 0
Dn Type= 1
Dn Known WS=1250.44
DSS Import GetInterval= 0
DSS Import GetPeak= 0
DSS Import FillOption= 0

--- GLADYFK.g01 (geometry) ---

Geom Title=Geometry
Program Version=6.31

River Reach=GLADYFK         ,Main
Reach XY= 30
2169342.34100001711955.4070000052169414.31100002712041.457000017
2169653.37300003711967.7690000092170049.05100003712128.536000013
2170161.19900002712214.2710000132170180.22900003712370.001000002
2170320.50600001712437.6220000092170665.04800002712286.985000014
2170698.87200002712350.142000005     2170958.108712335.174999997
     2170971.529712471.8760000172171210.64800002712622.942000002
2171513.12299998713323.327999994     2171857.979713377.613000005
2172041.52500001713652.4730000052172065.41899998713989.688999996
2171915.29800002714247.9229999932172028.76200002714423.199000001
2172062.41500004714743.788000003     2171869.111 715530.51000002
     2172090.745715889.8460000162172265.01900001716402.422000021
2172026.18600003716807.8589999972172187.86900002717150.083000019
      2172099.73717459.1969999972172225.32799999718008.231000021
2172075.17800002      718352.772     2171810.447718614.069000006
2171688.28400004718662.5450000022171389.82671208718570.855522095

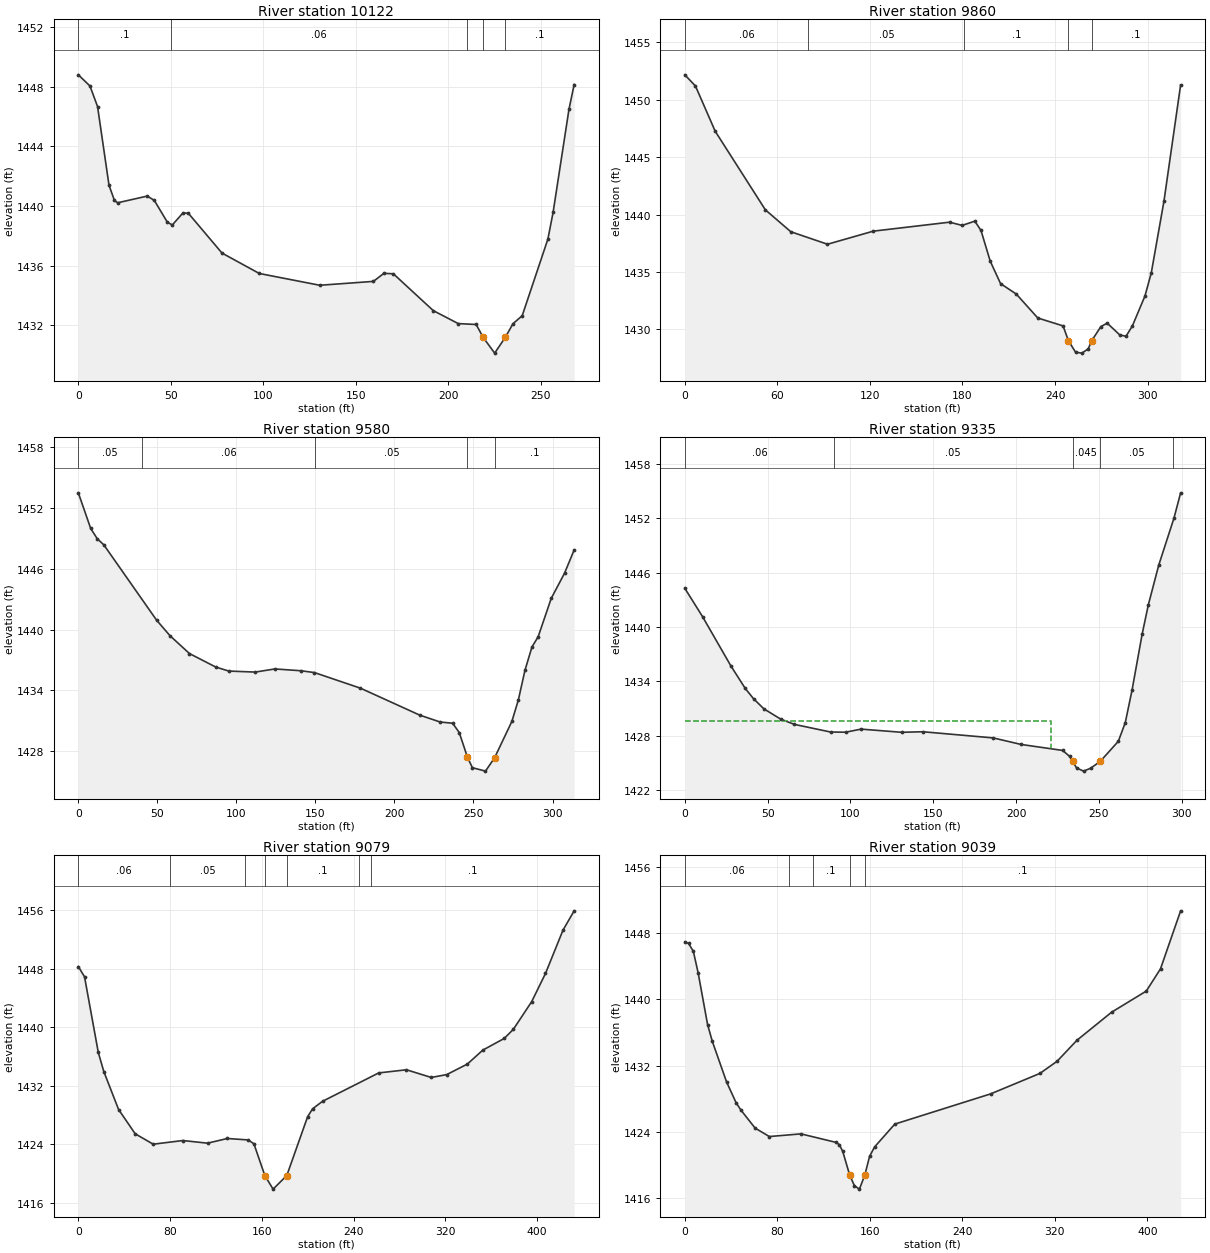
Type RM Length L Ch R = 1 ,10122   ,262.1,262.1,262.1
XS GIS Cut Line= 2
2169163.12460855 712091.352683732169378.76496317711931.913974117
#Sta/Elev= 30
       0  1448.8     6.3 1448.05    10.4 1446.67    16.6 1441.39    19.5 1440.39
    21.2 1440.22    37.3 1440.67    41.1 1440.38    48.1 1438.93    50.8 1438.73
    56.6 1439.54    59.5 1439.52    77.7 1436.85    97.9 1435.48   130.6 1434.69
   159.6 1434.95   165.3 1435.49   170.4 1435.46     192 1432.99   205.5 1432.12
   215.2 1432.06     219 1431.19   225.2 1430.14  230.92 1431.19   235.1 1432.11
   240.1 1432.65     254 1437.79   256.8 1439.57   265.4 1446.49   268.2 1448.15
#Mann= 5 ,-1,0
       0      .1       0      50     .06       0     210      .1       0
     219    .045       0  230.92      .1       0
Bank Sta=219,230.92
XS Rating Curve= 0 ,0
Exp/Cntr(USF)=0,0
Exp/Cntr=0.3,0.1

Type RM Length L Ch R = 1 ,9860    ,273.8,279.9,285.4
XS GIS Cut Line= 3
2169523.04460733712239.9138608472169561.50392696712083.262485734
2169528.67280044711926.611110622
#Sta/Elev= 30
       0 1452.17     6.9  1451.2    19.7 1447.26    52.2 1440.42    68.7 1438.51
    92.5 1437.42   122.2 1438.56   171.6 1439.34   179.8 1439.06     188 1439.43
     192 1438.62     198 1435.94   204.7 1433.99   214.9 1433.08   228.8    1431
   245.2 1430.31   248.71429.012   253.3 1428.02   257.4 1427.94   261.5 1428.31
   263.81429.026   269.7 1430.25   273.8 1430.55     282 1429.52     286 1429.41
   290.1  1430.3   298.3 1432.92   302.4 1434.94   310.6 1441.17   321.4 1451.29
#Mann= 5 ,-1,0
       0     .06       0      80     .05       0   181.3      .1       0
   248.7    .045       0   263.8      .1       0
Bank Sta=248.7,263.8
XS Rating Curve= 0 ,0
Exp/Cntr(USF)=0,0
Exp/Cntr=0.3,0.1

Type RM Length L Ch R = 1 ,9580    ,244,244.4,244.6
XS GIS Cut Line= 2
2169716.31861189712300.6937142612169803.27419556711999.303972803
#Sta/Elev= 30
       0 1453.51     7.8    1450      12 1448.97    16.1 1448.38    49.5 1440.94
      58  1439.4    70.3 1437.64    86.9 1436.31    95.2 1435.91   111.9 1435.81
   124.4 1436.12     141 1435.94   149.4 1435.76   178.5 1434.22     216 1431.56
   228.9 1430.88   236.8 1430.76     241 1429.84  246.161427.416   249.3 1426.37
   257.6 1426.03  263.391427.358   274.3 1430.94   278.4 1433.06   282.6    1436
     287 1438.29   290.9 1439.29   299.2 1443.09   307.6 1445.57   313.7 1447.87
#Mann= 5 ,-1,0
       0     .05       0      40     .06       0     150     .05       0
  246.16    .045       0  263.39      .1       0
Bank Sta=246.16,263.39
XS Rating Curve= 0 ,0
Exp/Cntr(USF)=0,0
Exp/Cntr=0.3,0.1

Type RM Length L Ch R = 1 ,9335    ,244.4,256.6,266.6
BEGIN DESCRIPTION:
Structure1 XS4
END DESCRIPTION:
XS GIS Cut Line= 3
2169940.49189874712343.1897170572170000.07865504712189.476784479
2170040.92580661712061.411654683
#Sta/Elev= 30
       0 1444.27    10.7 1441.15    27.9 1435.69    36.5 1433.23    41.5  1432.1
    47.7 1430.99    57.9 1429.85    66.2 1429.27      88 1428.43    97.1 1428.41
   106.4 1428.75   130.9  1428.4   143.7 1428.46   186.2 1427.78     203 1427.06
   228.1  1426.4   232.3 1425.74  234.081425.206   236.5 1424.47   240.7 1424.12
   244.9 1424.43  250.791425.195   261.7 1427.41   265.9 1429.47     270 1433.07
   276.1 1439.24   279.8 1442.44   286.1 1446.83   295.3 1452.01   299.3 1454.79
#Mann= 5 ,-1,0
       0     .06       0      90     .05       0  234.08    .045       0
  250.79     .05       0  294.86      .1       0
#XS Ineff= 2 , 0
          221.01 1429.68
Permanent Ineff=
       F       F
Bank Sta=234.08,250.79
XS Rating Curve= 0 ,0
Exp/Cntr(USF)=0,0
Exp/Cntr=0.3,0.1

Type RM Length L Ch R = 1 ,9079    ,40.4,40,39.6
XS GIS Cut Line= 4
2170057.69548201712429.7545521052170107.99371203712304.373456986
2170280.75719775712235.122270729 2170288.0467963712124.320372718
#Sta/Elev= 30
       0 1448.29     5.4  1446.9    17.4 1436.56    22.2 1433.95    35.1 1428.76
    49.6 1425.44    65.3 1424.02    91.1 1424.52   112.7 1424.16   129.9  1424.8
   148.2  1424.6   153.1 1424.07   162.61419.738   169.8 1417.88  181.761419.741
   199.9 1427.77   204.2 1428.85   212.9 1429.88   261.9 1433.76   286.1 1434.19
   307.7 1433.14   321.2 1433.53   339.2 1434.97   352.6 1436.87   371.3 1438.47
   379.3 1439.72   395.3 1443.51   407.3 1447.35   422.6 1453.28   432.3 1455.91
#Mann= 7 ,-1,0
       0     .06       0      80     .05       0  145.09      .1       0
   162.6    .045       0  181.76      .1       0  245.09     .05       0
  255.09      .1       0
Bank Sta=162.6,181.76
XS Rating Curve= 0 ,0
Exp/Cntr(USF)=0,0
Exp/Cntr=0.3,0.1

Type RM Length L Ch R = 1 ,9039    ,24.5,24.6,24.7
BEGIN DESCRIPTION:
Structure1 XS3
END DESCRIPTION:
XS GIS Cut Line= 4
2170091.50669036712444.4117351712170113.82239165712346.463605578
2170293.18361042712268.0616841462170302.56393228712135.799145877
#Sta/Elev= 30
       0 1446.94     3.3 1446.75     7.4 1445.79    11.5 1443.23    19.7 1436.96
    23.8 1434.93    36.1 1430.04    44.3 1427.54    48.4 1426.66    60.8 1424.46
    73.1 1423.44   100.5 1423.76   130.6 1422.74   133.6 1422.47   136.6 1421.64
  142.651418.762   146.7  1417.5     151 1417.09  155.661418.779   159.8 1421.04
   164.1 1422.18   181.6 1424.94   264.5 1428.59   307.1 1431.06     322 1432.53
   339.1 1435.06   369.1 1438.45   399.1    1441   411.4 1443.69   428.8 1450.69
#Mann= 5 ,-1,0
       0     .06       0      90     .05       0  110.46      .1       0
  142.65    .045       0  155.66      .1       0
Bank Sta=142.65,155.66
XS Rating Curve= 0 ,0
Exp/Cntr(USF)=0,0
Exp/Cntr=0.3,0.1

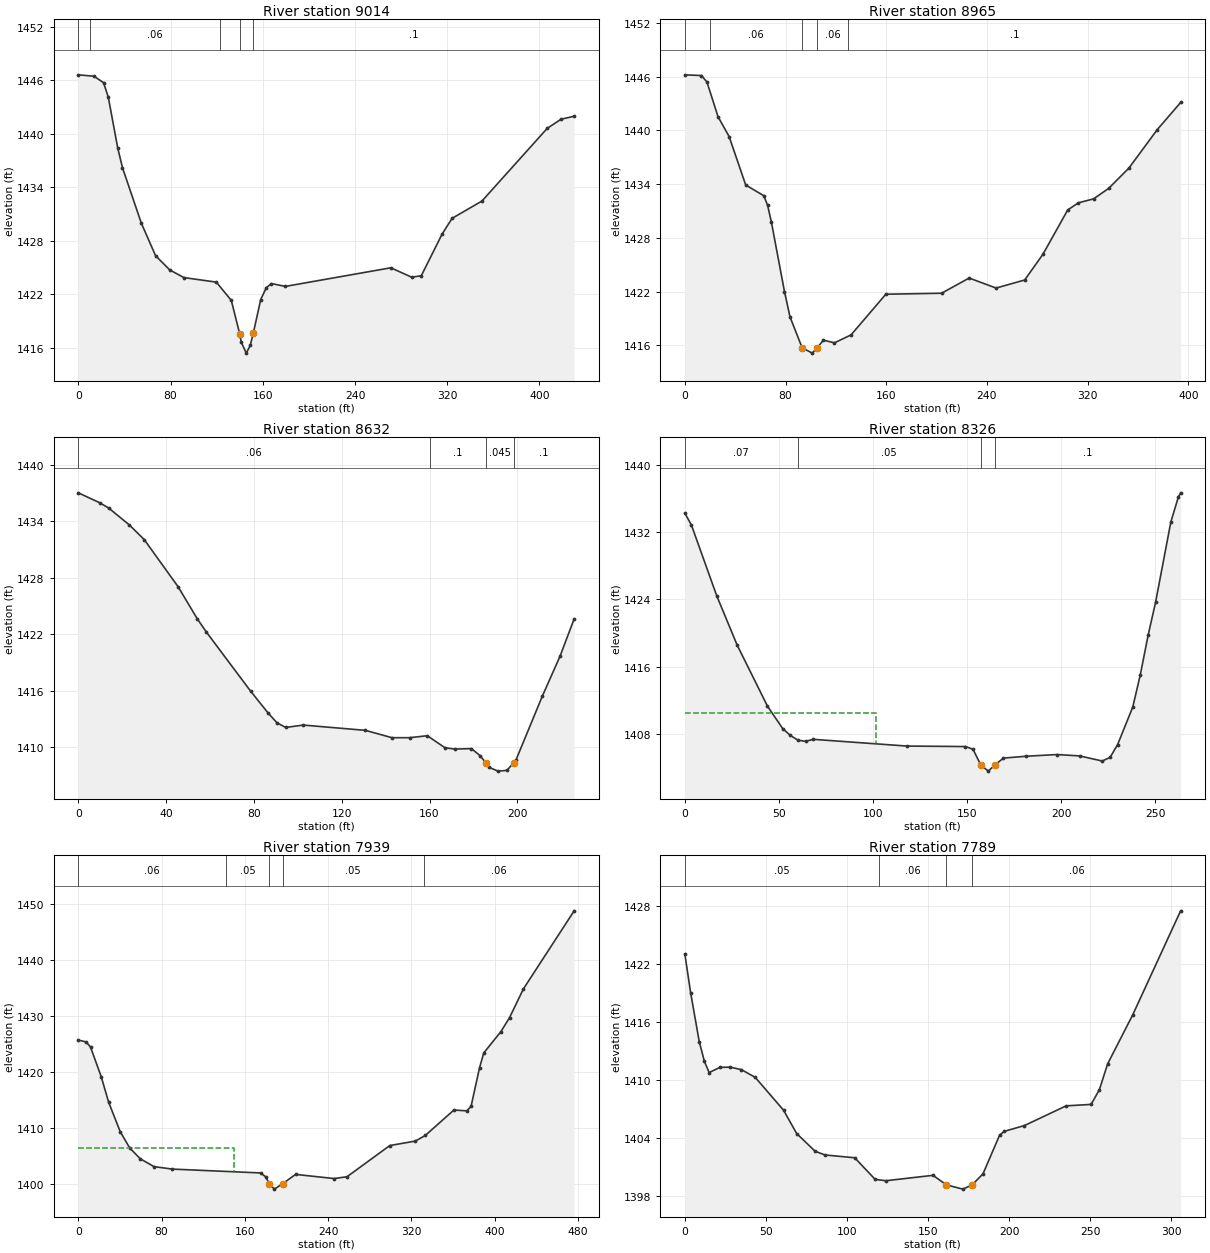
Type RM Length L Ch R = 1 ,9014    ,56.7,49,40.5
BEGIN DESCRIPTION:
Structure1 XS2
END DESCRIPTION:
XS GIS Cut Line= 4
2170106.17135089712466.5806531832170128.48705218712366.416929088
2170307.84827094712290.2306021582170317.22859281 712157.96806389
#Sta/Elev= 30
       0 1446.63    13.7 1446.47    21.9 1445.74      26 1444.12    34.2  1438.4
    38.3  1436.2    54.7 1429.96      67 1426.33    79.3 1424.73    91.6 1423.87
   119.7 1423.36   132.7 1421.31   139.9 1417.59   141.4  1416.6   145.7 1415.39
   149.1 1416.25  151.711417.594   158.2  1421.4   163.1 1422.74   167.5  1423.2
   179.6 1422.88   271.1 1424.97   289.2 1423.91   297.5 1424.08   315.5 1428.74
   324.2 1430.52   350.1 1432.46   406.8 1440.63   418.8 1441.65   430.1 1441.98
#Mann= 5 ,-1,0
       0     .05       0      10     .06       0  122.62      .1       0
   139.9    .045       0  151.71      .1       0
Bank Sta=139.9,151.71
XS Rating Curve= 0 ,0
Exp/Cntr(USF)=0,0
Exp/Cntr=0.3,0.1

Type RM Length L Ch R = 1 ,8965    ,337.8,333.4,325.3
XS GIS Cut Line= 4
2170156.83402234712477.1369427022170223.67074776712332.050823462
2170324.58583615712287.5716612812170336.39498581712164.231653757
#Sta/Elev= 30
       0 1446.21    13.2 1446.13    17.6 1445.41    26.4 1441.53    35.2 1439.32
    48.4  1433.9    62.8  1432.7    65.8 1431.63    68.8 1429.75    79.2 1421.99
    83.6 1419.16    93.21415.726   101.2 1415.12  105.271415.733   110.1 1416.57
   118.9 1416.27   132.1 1417.16   159.7  1421.7     204 1421.81   225.9 1423.51
   247.3 1422.39     270 1423.29   284.5 1426.16   304.2 1431.11   312.6 1431.91
   324.7 1432.35   336.7 1433.52   352.8 1435.79   375.3 1440.08   393.9 1443.12
#Mann= 5 ,-1,0
       0     .05       0      20     .06       0    93.2    .045       0
  105.27     .06       0     130      .1       0
Bank Sta=93.2,105.27
XS Rating Curve= 0 ,0
Exp/Cntr(USF)=0,0
Exp/Cntr=0.3,0.1

Type RM Length L Ch R = 1 ,8632    ,301.2,305.9,307.1
BEGIN DESCRIPTION:
Structure1 XS1
END DESCRIPTION:
XS GIS Cut Line= 2
2170493.82600292712518.9263574192170465.68503733712294.736664893
#Sta/Elev= 30
       0 1437.04     9.8 1435.98    13.9 1435.41    23.2 1433.64      30 1432.08
    45.4 1427.09    54.2 1423.66    58.2  1422.3    78.5 1415.98    86.4 1413.68
    90.5 1412.62    94.5 1412.13   102.5 1412.38   130.8 1411.82   142.9 1411.04
   150.9 1411.04     159 1411.25     167 1409.98   171.4 1409.83   179.1 1409.88
   183.2  1409.1  185.611408.371   187.2 1407.89   191.2 1407.49   195.3 1407.57
   198.3 1408.38   199.3 1408.62   211.4 1415.45   219.5 1419.71   225.9 1423.66
#Mann= 4 ,-1,0
       0     .06       0     160      .1       0  185.61    .045       0
   198.3      .1       0
Bank Sta=185.61,198.3
XS Rating Curve= 0 ,0
Exp/Cntr(USF)=0,0
Exp/Cntr=0.3,0.1

Type RM Length L Ch R = 1 ,8326    ,369.9,386.2,396.6
XS GIS Cut Line= 2
2170696.31699937712512.6529365532170734.53312548712252.088440358
#Sta/Elev= 30
       0 1434.25     3.5 1432.84      17  1424.4    27.8 1418.57    43.9 1411.31
      52 1408.64    56.1 1407.82    60.1 1407.26    64.2 1407.12    68.2 1407.36
     118 1406.56   149.1  1406.5   153.1 1406.18  157.141404.352   161.2 1403.58
  164.831404.333   169.3 1405.13   181.4 1405.35   197.6 1405.55   209.7 1405.39
   221.8 1404.78   225.9 1405.21   229.9 1406.72     238 1411.21     242 1415.05
   246.2  1419.8   250.1 1423.65   258.2 1433.19   262.2 1436.17   263.4 1436.66
#Mann= 4 ,-1,0
       0     .07       0      60     .05       0  157.14    .045       0
  164.83      .1       0
#XS Ineff= 2 , 0
          101.65 1410.43
Permanent Ineff=
       F       F
Bank Sta=157.14,164.83
XS Rating Curve= 0 ,0
Exp/Cntr(USF)=0,0
Exp/Cntr=0.3,0.1

Type RM Length L Ch R = 1 ,7939    ,156,151,146.9
BEGIN DESCRIPTION:
Structure2 XS4
END DESCRIPTION:
XS GIS Cut Line= 3
2170830.08103251712555.9564396922170866.38287812712471.533542925
2171240.62178151712382.961353834
#Sta/Elev= 30
       0 1425.77     7.4 1425.45    11.7 1424.54      22 1419.23    29.1  1414.7
    40.2 1409.44    49.4  1406.5    59.6 1404.57    72.7 1403.18    90.1 1402.74
   175.1 1402.05   180.1 1401.35183.48941400.145   188.4 1399.16196.5993 1400.16
   208.8 1401.79   245.8 1401.05   258.2 1401.37   299.3 1406.94   323.9 1407.74
   333.5 1408.75   360.9 1413.28   373.3 1413.14   377.4 1413.92   385.6 1420.86
   389.7  1423.5   406.1 1427.28   414.4 1429.78   427.7  1434.9   476.5 1448.85
#Mann= 5 ,-1,0
       0     .06       0   141.9     .05       0183.4894    .045       0
196.5993     .05       0   331.9     .06       0
#XS Ineff= 2 , 0
          149.61 1406.54
Permanent Ineff=
       F       F
Bank Sta=183.4894,196.5993
XS Rating Curve= 0 ,0
Exp/Cntr(USF)=0,0
Exp/Cntr=0.3,0.1

Type RM Length L Ch R = 1 ,7789    ,80.2,69.6,67.2
XS GIS Cut Line= 2
2170944.69084525712630.7586715762171183.29471406712439.450447141
#Sta/Elev= 30
       0 1423.07     3.6 1419.04     8.9 1413.97    12.1 1411.92      15 1410.76
    21.7  1411.3    28.1 1411.32    34.9 1411.06    43.4 1410.27    60.9 1406.86
      69 1404.44    80.4  1402.6    86.5 1402.22   104.8 1401.93   117.4 1399.69
     124 1399.55   153.1 1400.11  161.361399.119   171.5 1398.68   177.2 1399.12
   183.9 1400.26   194.2 1404.29   197.1 1404.67   209.5 1405.27   235.2 1407.31
   250.6 1407.46   255.7 1408.99   260.8 1411.67   276.2 1416.72   305.8 1427.52
#Mann= 4 ,-1,0
       0     .05       0     120     .06       0  161.36    .045       0
   177.2     .06       0
Bank Sta=161.36,177.2
XS Rating Curve= 0 ,0
Exp/Cntr(USF)=0,0
Exp/Cntr=0.3,0.1

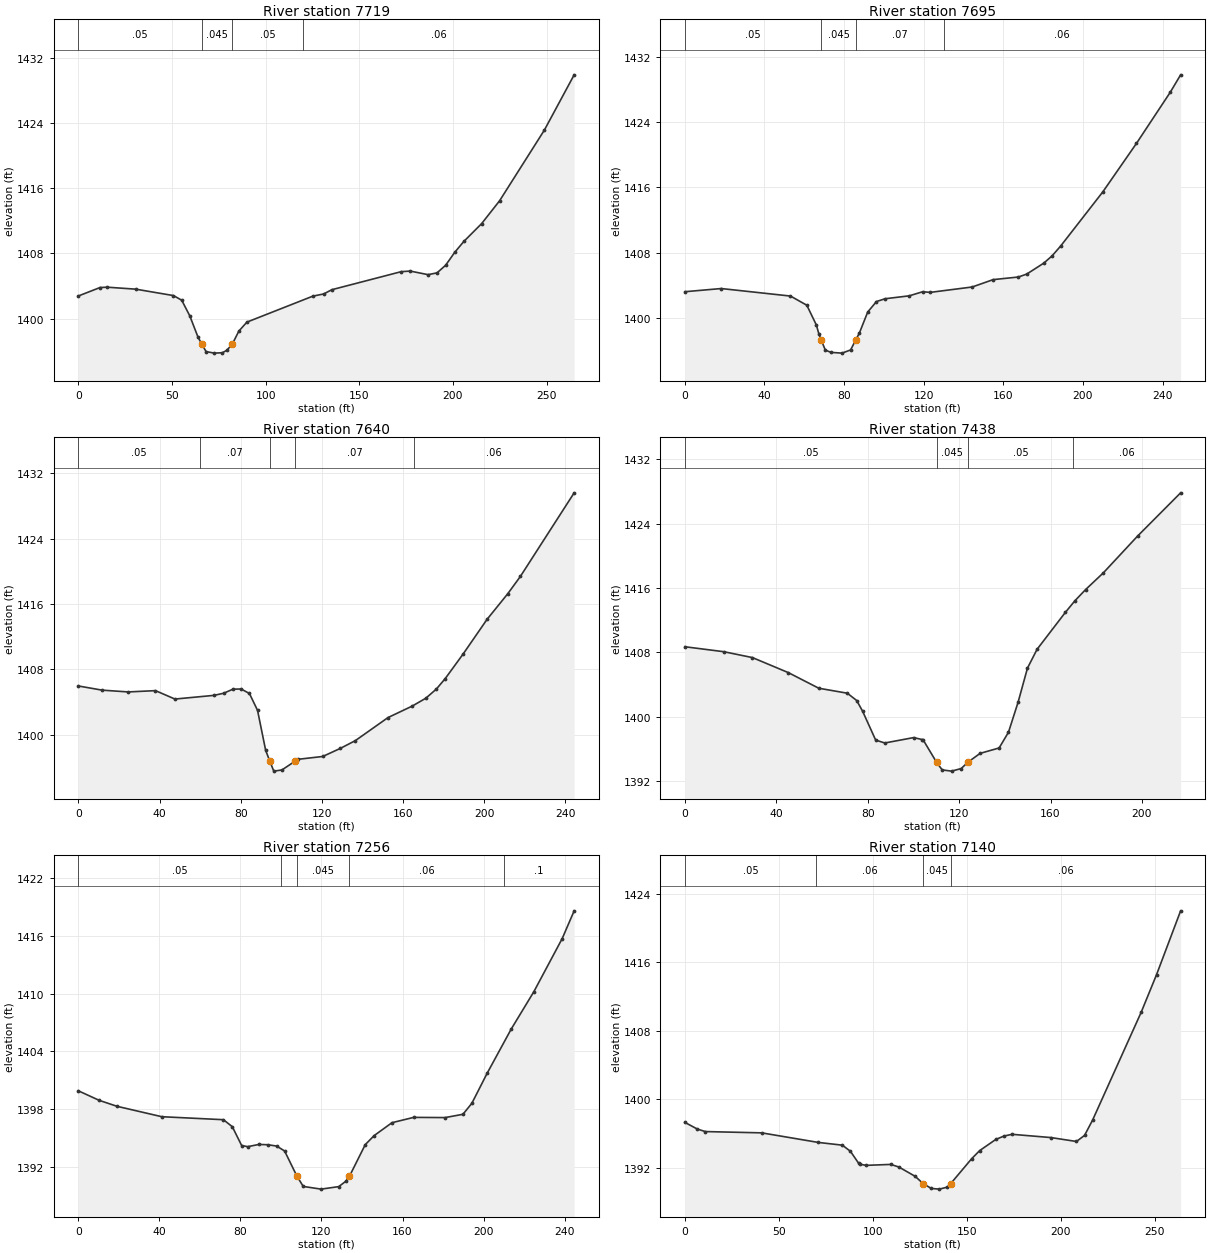
Type RM Length L Ch R = 1 ,7719    ,24,23.8,25
BEGIN DESCRIPTION:
Structure2 XS3
END DESCRIPTION:
XS GIS Cut Line= 3
2171050.65749082712663.8507076242171114.07337105712516.599396131
2171201.52493927712459.623938336
#Sta/Elev= 30
       0 1402.77    11.6 1403.81    15.4 1403.85    30.6 1403.61    50.8 1402.82
    55.2 1402.25    59.5 1400.33    63.9 1397.71    65.81396.906    68.2 1395.94
    72.6 1395.75    76.9  1395.8    79.3  1396.1    82.3  1396.9    85.7 1398.46
      90 1399.56   125.2 1402.75     131 1403.02   135.3 1403.54   172.4 1405.76
   177.2 1405.83   186.7 1405.39   191.5 1405.61   196.1 1406.55     201 1408.15
   205.8 1409.47   215.3 1411.66   224.9 1414.47   248.8 1423.15   264.7 1429.94
#Mann= 4 ,-1,0
       0     .05       0    65.8    .045       0    82.3     .05       0
     120     .06       0
Bank Sta=65.8,82.3
XS Rating Curve= 0 ,0
Exp/Cntr(USF)=0,0
Exp/Cntr=0.3,0.1

Type RM Length L Ch R = 1 ,7695    ,57.5,54.8,50.4
BEGIN DESCRIPTION:
Structure2 XS2
END DESCRIPTION:
XS GIS Cut Line= 3
2171073.37056071712674.290568097 2171129.4300071 712537.60347968
2171225.16557203 712504.17201256
#Sta/Elev= 30
       0 1403.24    18.3 1403.63    53.1 1402.71    61.3 1401.59    66.1 1399.17
    67.4 1398.04   68.561397.319    70.6  1396.1    73.5 1395.82      79 1395.73
    83.3 1396.1285.831861397.315    87.7 1398.18    91.9 1400.76    96.3 1402.04
   100.6 1402.38   112.8 1402.74   119.5 1403.24   123.3 1403.16   144.4 1403.82
   154.9 1404.72   167.6 1405.04   171.8  1405.4   180.3 1406.73   184.5 1407.62
   188.8 1408.82     210 1415.45   226.9 1421.38   243.9 1427.64   249.1 1429.77
#Mann= 4 ,-1,0
       0     .05       0   68.56    .045       085.83186     .07       0
     130     .06       0
Bank Sta=68.56,85.83186
XS Rating Curve= 0 ,0
Exp/Cntr(USF)=0,0
Exp/Cntr=0.3,0.1

Type RM Length L Ch R = 1 ,7640    ,190.1,202.1,217.1
XS GIS Cut Line= 4
2171109.70913251 712704.865459432171151.25984426 712642.17491187
2171160.73632238712549.5970102422171229.98750864712518.251736463
#Sta/Elev= 30
       0 1405.98    11.7 1405.47    24.6 1405.25      38 1405.41    47.6 1404.38
    66.8 1404.83    71.6 1405.09    76.2 1405.59    80.2 1405.61    84.3 1405.06
    88.3    1403    92.3 1398.11    94.31396.816    96.3 1395.57   100.3 1395.71
     107 1396.82   108.4 1397.02   120.4 1397.36   129.1 1398.35   136.5  1399.3
   152.6 1402.12   164.5 1403.52   171.2 1404.48   176.4  1405.6   180.8 1406.89
   189.6 1409.89   201.4 1414.13   211.6 1417.26   217.8 1419.37   244.3 1429.59
#Mann= 5 ,-1,0
       0     .05       0      60     .07       0    94.3    .045       0
     107     .07       0  165.21     .06       0
Bank Sta=94.3,107
XS Rating Curve= 0 ,0
Exp/Cntr(USF)=0,0
Exp/Cntr=0.3,0.1

Type RM Length L Ch R = 1 ,7438    ,183.9,182,180.2
BEGIN DESCRIPTION:
Structure2 XS1
END DESCRIPTION:
XS GIS Cut Line= 2
2171135.66483252712788.3667393112171344.68014995712730.584822067
#Sta/Elev= 30
       0 1408.69    17.1 1408.07    29.6 1407.34    45.3 1405.47    58.6 1403.53
    71.1 1402.91    75.2    1402    77.8 1400.66    83.5 1397.08    87.5 1396.72
   100.1 1397.39   103.8 1397.15   104.3 1397.09110.15371394.311   112.6 1393.37
   116.7 1393.22   120.9 1393.54123.8536 1394.33   129.2 1395.43   137.5  1396.1
   141.6 1398.06   145.8 1401.79   149.9 1406.03   154.1 1408.37   166.5 1412.97
   170.7 1414.42   175.3 1415.79   183.1 1417.88   198.1 1422.46   216.9 1427.83
#Mann= 4 ,-1,0
       0     .05       0110.1537    .045       0123.8536     .05       0
     170     .06       0
#XS Ineff= 2 , 0
                          354.79         1399.57
Permanent Ineff=
       F       F
Bank Sta=110.1537,123.8536
XS Rating Curve= 0 ,0
Exp/Cntr(USF)=0,0
Exp/Cntr=0.3,0.1

Type RM Length L Ch R = 1 ,7256    ,115.8,116,116.1
BEGIN DESCRIPTION:
Structure3 XS4
END DESCRIPTION:
XS GIS Cut Line= 2
2171206.72915757 712974.136806452171430.37691759712874.763843296
#Sta/Elev= 30
       0  1399.9    10.3 1398.91    19.1 1398.29    41.2 1397.21    71.6  1396.9
      76 1396.17    80.6 1394.22    83.6  1394.1    89.1 1394.33    93.5  1394.3
    97.9 1394.16   101.8 1393.65107.86131391.046     111 1389.97   119.8 1389.69
   128.5 1389.95   132.1 1390.52133.82121391.035   141.6 1394.31     146 1395.25
   154.8 1396.59   165.5 1397.14     181 1397.12   189.8 1397.46   194.2  1398.6
   201.8 1401.74   213.6  1406.3   224.8 1410.19   238.8 1415.71   244.7 1418.59
#Mann= 5 ,-1,0
       0     .05       0     100     .06       0107.8613    .045       0
133.8212     .06       0     210      .1       0
Bank Sta=107.8613,133.8212
XS Rating Curve= 0 ,0
Exp/Cntr(USF)=0,0
Exp/Cntr=0.3,0.1

Type RM Length L Ch R = 1 ,7140    ,42.9,42.8,43.2
BEGIN DESCRIPTION:
Structure3 XS3
END DESCRIPTION:
XS GIS Cut Line= 2
2171246.06088716713075.8894946082171491.75433225712980.147706201
#Sta/Elev= 30
       0 1397.29     6.6 1396.51    10.9 1396.21    40.9 1396.06      71 1394.94
    83.8 1394.62    88.1  1393.9    92.4 1392.52    93.3 1392.39    96.4 1392.26
   109.6 1392.37   113.9 1392.06   122.5 1390.98126.73831390.132   131.1 1389.56
   135.4 1389.48   139.7 1389.72141.42831390.129   152.5 1393.02   156.8 1393.98
   165.4 1395.29   169.7 1395.68     174 1395.89   194.7 1395.51   208.3 1395.05
   212.6 1395.76   216.9 1397.56   242.7 1410.15   250.9 1414.56   263.7 1422.02
#Mann= 4 ,-1,0
       0     .05       0      70     .06       0126.7383    .045       0
141.4283     .06       0
Bank Sta=126.7383,141.4283
XS Rating Curve= 0 ,0
Exp/Cntr(USF)=0,0
Exp/Cntr=0.3,0.1

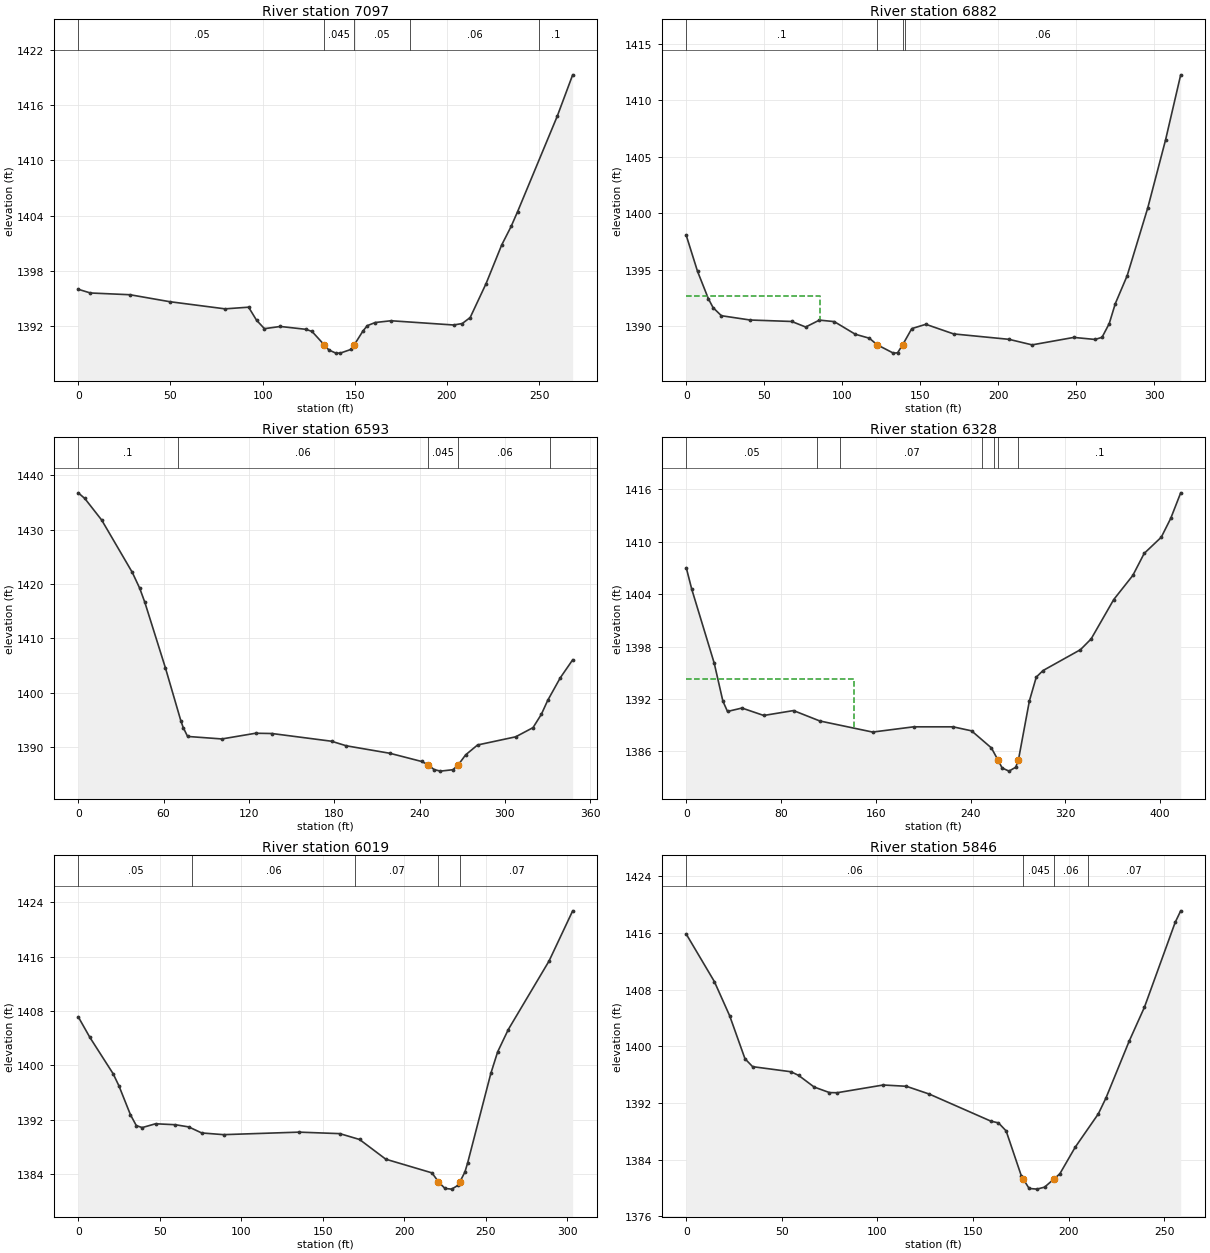
Type RM Length L Ch R = 1 ,7097    ,216.7,215.8,213.7
BEGIN DESCRIPTION:
Structure3 XS2
END DESCRIPTION:
XS GIS Cut Line= 2
2171262.00323919713114.8596884742171512.02045973713017.784800096
#Sta/Elev= 30
       0 1396.03     6.6 1395.63    28.1 1395.44    49.5 1394.69    79.6 1393.91
    92.4 1394.09    96.7 1392.68     101 1391.76   109.6    1392   123.5 1391.69
   126.8 1391.46133.51151389.986   135.9 1389.46   139.6 1389.12   142.1 1389.11
   148.2 1389.53  149.681389.998   154.4  1391.5   156.8 1392.09   161.1 1392.43
   169.7 1392.62   203.6 1392.16   208.3 1392.32   212.6 1392.97   221.2 1396.64
   229.7 1400.84   234.8 1402.84   238.3 1404.44   259.8 1414.78   268.2 1419.28
#Mann= 5 ,-1,0
       0     .05       0133.5115    .045       0  149.68     .05       0
     180     .06       0     250      .1       0
Bank Sta=133.5115,149.68
XS Rating Curve= 0 ,0
Exp/Cntr(USF)=0,0
Exp/Cntr=0.3,0.1

Type RM Length L Ch R = 1 ,6882    ,295.7,288.5,279.7
BEGIN DESCRIPTION:
Structure3 XS1
END DESCRIPTION:
XS GIS Cut Line= 2
2171376.28150752  713312.52324942171656.75313123 713165.25219615
#Sta/Elev= 30
       0 1398.05     7.2 1394.88    14.2 1392.44    17.2 1391.66    22.5 1390.95
    40.9 1390.57    67.6 1390.44    76.5 1389.95    85.3 1390.56    94.8 1390.43
   108.3 1389.31   117.3 1388.96  122.281388.382   132.7 1387.64   135.4 1387.67
   138.7 1388.39   144.5 1389.81   153.5 1390.19   171.3 1389.34   206.8 1388.86
   221.6 1388.37   248.3 1389.03   261.9 1388.85   266.4 1389.04     271 1390.25
   274.9 1392.02   282.5 1394.49   295.7 1400.49   307.1  1406.5   316.8 1412.26
#Mann= 4 ,-1,0
       0      .1       0  122.28    .045       0   138.7      .1       0
     140     .06       0
#XS Ineff= 2 , 0
           85.86 1392.66
Permanent Ineff=
       F       F
Bank Sta=122.28,138.7
XS Rating Curve= 0 ,0
Exp/Cntr(USF)=0,0
Exp/Cntr=0.3,0.1

Type RM Length L Ch R = 1 ,6593    ,258.7,265.4,266.5
XS GIS Cut Line= 3
2171554.98885414713529.0023011642171662.08295634713369.711073515
2171729.57923925713229.318805079
#Sta/Elev= 30
       0 1436.77     4.6 1435.73    16.5 1431.75      38 1422.13    43.2 1419.22
    46.8 1416.64    61.3 1404.56    72.1 1394.87    73.8 1393.59    76.9 1391.95
     101 1391.49   124.7 1392.54   136.2 1392.49   178.1 1391.07   188.5 1390.23
   219.2 1388.85   241.4 1387.35  246.041386.749   250.2 1385.86   254.7 1385.57
   263.5 1385.83  267.351386.766   272.4 1388.56   280.8 1390.38   307.6 1391.88
   319.8 1393.57   325.7 1396.04   330.1 1398.57     339 1402.75   347.7 1406.05
#Mann= 5 ,-1,0
       0      .1       0      70     .06       0  246.04    .045       0
  267.35     .06       0  331.94      .1       0
Bank Sta=246.04,267.35
XS Rating Curve= 0 ,0
Exp/Cntr(USF)=0,0
Exp/Cntr=0.3,0.1

Type RM Length L Ch R = 1 ,6328    ,299.2,309.1,315.9
XS GIS Cut Line= 3
2171718.69258196713630.1553711982171935.30400671713406.496669927
 2171927.5752115713300.878050797
#Sta/Elev= 30
       0 1407.02     4.6 1404.58    23.6  1396.1    30.9 1391.76    34.8 1390.58
      47 1390.97    65.4 1390.12    90.5 1390.68   112.7 1389.49   157.3 1388.22
   191.9 1388.82   225.2 1388.82   240.8 1388.36   257.5 1386.41   263.1 1385.02
   266.6 1384.11   272.4 1383.75   278.1  1384.2   280.41385.072   289.6 1391.79
   295.4 1394.51   301.1 1395.26   332.7 1397.65   341.7 1398.88   360.8 1403.39
   376.9 1406.15   386.5 1408.67   400.9 1410.52   408.9 1412.68   417.3  1415.6
#Mann= 7 ,-1,0
       0     .05       0     110     .06       0     130     .07       0
     250     .08       0     260      .1       0   263.1    .045       0
   280.4      .1       0
#XS Ineff= 2 , 0
          141.36 1394.26
Permanent Ineff=
       F       F
Bank Sta=263.1,280.4
XS Rating Curve= 0 ,0
Exp/Cntr(USF)=0,0
Exp/Cntr=0.3,0.1

Type RM Length L Ch R = 1 ,6019    ,171.7,172.4,172.5
XS GIS Cut Line= 2
2171825.16229158713726.1285331712172125.70780407 713686.44977169
#Sta/Elev= 30
       0 1407.14     7.1 1404.13    21.4 1398.77    24.9 1397.02      32 1392.75
    35.6 1391.15    39.2 1390.86    47.4 1391.42    59.5 1391.28    67.7 1390.96
    75.7 1390.07    89.1 1389.82   135.4 1390.19   160.4 1389.97   172.5 1389.11
   188.6 1386.21   216.9  1384.2   220.9 1382.89   220.9 1382.87   224.9 1381.91
     229 1381.81     233 1382.39  234.081382.906   237.1 1384.32   238.8 1385.68
     253 1398.82   257.2    1402   263.7 1405.27   288.7 1415.35   303.2 1422.73
#Mann= 5 ,-1,0
       0     .05       0      70     .06       0     170     .07       0
   220.9    .045       0  234.08     .07       0
Bank Sta=220.9,234.08
XS Rating Curve= 0 ,0
Exp/Cntr(USF)=0,0
Exp/Cntr=0.3,0.1

Type RM Length L Ch R = 1 ,5846    ,229.2,248.3,268
BEGIN DESCRIPTION:
Structure4 XS4
END DESCRIPTION:
XS GIS Cut Line= 2
2171877.57989044 713884.491270162172135.06972558713860.852859066
#Sta/Elev= 30
       0 1415.83    14.7 1409.13    22.7  1404.3    30.7 1398.24    34.7 1397.12
    54.8  1396.4    58.8 1395.88    66.9 1394.24    74.9 1393.46    78.9 1393.44
     103 1394.53   115.1 1394.35   127.1 1393.25   159.3 1389.43   163.3 1389.18
   167.3 1388.05   175.3 1381.66  176.191381.289   179.3 1379.93   183.4 1379.83
   187.4 1380.11  192.371381.273   195.4    1382   203.4 1385.74   215.5 1390.45
   219.5 1392.69   231.6 1400.69   239.6 1405.49   255.7 1417.48   258.6 1419.12
#Mann= 4 ,-1,0
       0     .06       0  176.19    .045       0  192.37     .06       0
     210     .07       0
Bank Sta=176.19,192.37
XS Rating Curve= 0 ,0
Exp/Cntr(USF)=0,0
Exp/Cntr=0.3,0.1

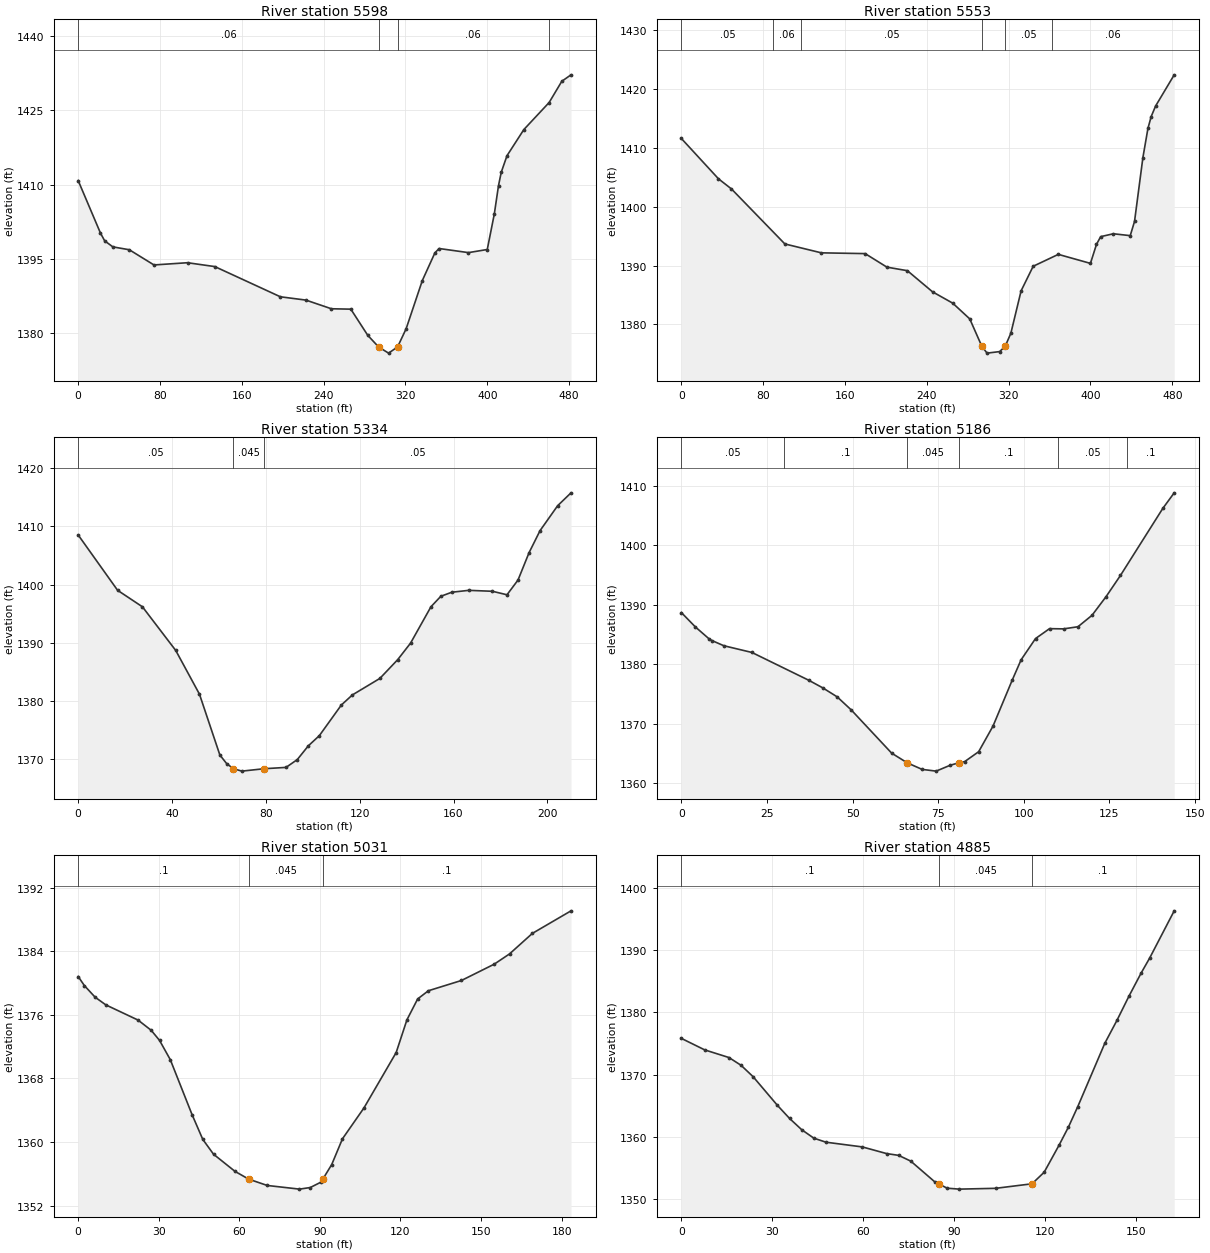
Type RM Length L Ch R = 1 ,5598    ,46.2,44.6,47.2
BEGIN DESCRIPTION:
Structure4 XS3
END DESCRIPTION:
XS GIS Cut Line= 5
2171878.42411941713916.5719709322171984.79696933 713906.44122332
2171990.70657211714022.1005918912172029.54110462714195.167530265
2172108.89862758 714174.90603504
#Sta/Elev= 30
       0 1410.84    21.8 1400.23    25.9 1398.67    33.9 1397.45      50 1396.87
    74.1  1393.8   106.9 1394.25   133.6 1393.47   197.7 1387.37   222.7  1386.7
   247.6 1384.95   266.6 1384.87   283.2 1379.57  293.831377.222   303.5 1375.99
  312.331377.245   320.7 1380.93   336.5 1390.65   348.8 1396.24   352.9 1397.12
   381.6 1396.29     400 1396.92   406.9  1404.1     411 1409.84   413.7 1412.54
   419.3 1415.87   435.8 1421.15   460.5 1426.61   472.9  1430.9   481.9  1432.2
#Mann= 4 ,-1,0
       0     .06       0  293.83    .045       0  312.33     .06       0
  460.03      .1       0
Bank Sta=293.83,312.33
XS Rating Curve= 0 ,0
Exp/Cntr(USF)=0,0
Exp/Cntr=0.3,0.1

Type RM Length L Ch R = 1 ,5553    ,240.4,219.7,182.4
BEGIN DESCRIPTION:
Structure4 XS2
END DESCRIPTION:
XS GIS Cut Line= 5
2171843.38861725713945.2757558332171949.76146717713935.145008221
2171955.67106995714050.8043767922171994.50560246714223.871315166
2172073.86312542714203.609819941
#Sta/Elev= 30
       0 1411.57    36.3 1404.72      49    1403   101.2 1393.66   136.9 1392.15
   179.7 1392.02     201 1389.72     221 1389.12   245.6 1385.53   265.3 1383.61
     282 1380.93   293.8 1376.28   298.9 1375.12   311.2 1375.38  316.651376.285
   322.2 1378.51   332.2  1385.7     344 1389.87   368.6 1391.89     400 1390.36
   405.9 1393.59     410  1394.9   422.4 1395.39   438.9 1395.07   443.1 1397.48
   451.3 1408.34   456.2 1413.27   459.4  1415.3   463.7 1417.08   481.9 1422.38
#Mann= 6 ,-1,0
       0     .05       0      90     .06       0  116.85     .05       0
   293.8    .045       0  316.65     .05       0  362.66     .06       0
Bank Sta=293.8,316.65
XS Rating Curve= 0 ,0
Exp/Cntr(USF)=0,0
Exp/Cntr=0.3,0.1

Type RM Length L Ch R = 1 ,5334    ,142.3,147.6,150
BEGIN DESCRIPTION:
Structure4 XS1
END DESCRIPTION:
XS GIS Cut Line= 2
2171896.85692539714352.9880949442172075.33537144714242.208369806
#Sta/Elev= 30
       0 1408.52    16.8 1399.02    27.4 1396.18    41.6 1388.68    51.7 1381.18
    60.4 1370.73    63.3 1369.25    66.2 1368.37    69.8 1367.96    79.2 1368.37
    88.6  1368.6    93.4 1369.94    98.1  1372.3   102.8 1374.05   112.2 1379.32
   116.9 1381.05   128.6 1383.88   136.2  1387.1   141.7 1389.95   150.4  1396.2
   154.6 1397.99   159.3 1398.69   166.5 1399.01   176.6 1398.85   182.8 1398.25
   187.5 1400.78   192.2 1405.47   196.9 1409.27   204.4 1413.55   210.1 1415.76
#Mann= 3 ,-1,0
       0     .05       0    66.2    .045       0    79.2     .05       0
Bank Sta=66.2,79.2
XS Rating Curve= 0 ,0
Exp/Cntr(USF)=0,0
Exp/Cntr=0.3,0.1

Type RM Length L Ch R = 1 ,5186    ,149.2,154.7,158.1
XS GIS Cut Line= 2
2171960.21451441714456.2467011732172099.35458164714419.658886424
#Sta/Elev= 30
       0 1388.69     4.1 1386.27     8.2 1384.22       9 1383.97    12.4 1383.12
    20.6 1381.99    37.2 1377.32    41.3 1376.04    45.5 1374.53    49.6 1372.34
    61.4 1365.08   65.951363.453    70.3 1362.35    74.4 1362.06    78.5 1363.05
    81.1 1363.47    82.7 1363.65    86.8 1365.32      91 1369.63    96.6 1377.34
    99.2 1380.76   103.4 1384.32   107.5 1385.99   111.6 1385.95   115.8 1386.31
   119.9 1388.23     124 1391.36   128.2 1394.92   140.6 1406.21   143.9  1408.8
#Mann= 6 ,-1,0
       0     .05       0      30      .1       0   65.95    .045       0
    81.1      .1       0     110     .05       0     130      .1       0
Bank Sta=65.95,81.1
XS Rating Curve= 0 ,0
Exp/Cntr(USF)=0,0
Exp/Cntr=0.3,0.1

Type RM Length L Ch R = 1 ,5031    ,144.8,146.1,146.5
XS GIS Cut Line= 3
2171989.84695118 714586.933345372172128.89146215714582.374508944
 2172156.2444807714617.325588206
#Sta/Elev= 30
       0 1380.82     2.3 1379.68     6.3 1378.22    10.3 1377.25    22.3 1375.34
    27.2 1374.05    30.3 1372.78    34.3 1370.36    42.4 1363.45    46.4 1360.33
    50.4 1358.47    58.4 1356.31   63.521355.331    70.4 1354.54    82.4 1354.08
    86.4 1354.28    90.4 1354.96   91.091355.339    94.4 1357.17    98.4 1360.41
   106.4 1364.29   118.4 1371.26   122.4 1375.37   126.4    1378   130.4 1379.03
   142.7 1380.32   154.9 1382.37   160.6 1383.66   169.1 1386.24   183.5 1389.08
#Mann= 3 ,-1,0
       0      .1       0   63.52    .045       0   91.09      .1       0
Bank Sta=63.52,91.09
XS Rating Curve= 0 ,0
Exp/Cntr(USF)=0,0
Exp/Cntr=0.3,0.1

Type RM Length L Ch R = 1 ,4885    ,165,173.9,182.9
XS GIS Cut Line= 2
2171964.46212363714728.2788416542172127.06062281714730.558259867
#Sta/Elev= 30
       0 1375.81     7.7 1373.96    15.7 1372.73    19.7 1371.48    23.7 1369.63
    31.7 1365.03    35.7 1362.93    39.7 1361.12    43.7 1359.76    47.7 1359.11
    59.7 1358.35    67.7 1357.28    71.7 1356.99    75.7 1356.06    83.7 1352.69
   85.041352.371    87.7 1351.71    91.7 1351.56   103.7 1351.69   115.7 1352.42
   119.7 1354.28   124.6 1358.62   127.7 1361.54   130.8 1364.85   139.7 1375.02
   143.7  1378.7   147.7 1382.63   151.7 1386.33   154.5 1388.73   162.6 1396.33
#Mann= 3 ,-1,0
       0      .1       0   85.04    .045       0   115.7      .1       0
Bank Sta=85.04,115.7
XS Rating Curve= 0 ,0
Exp/Cntr(USF)=0,0
Exp/Cntr=0.3,0.1