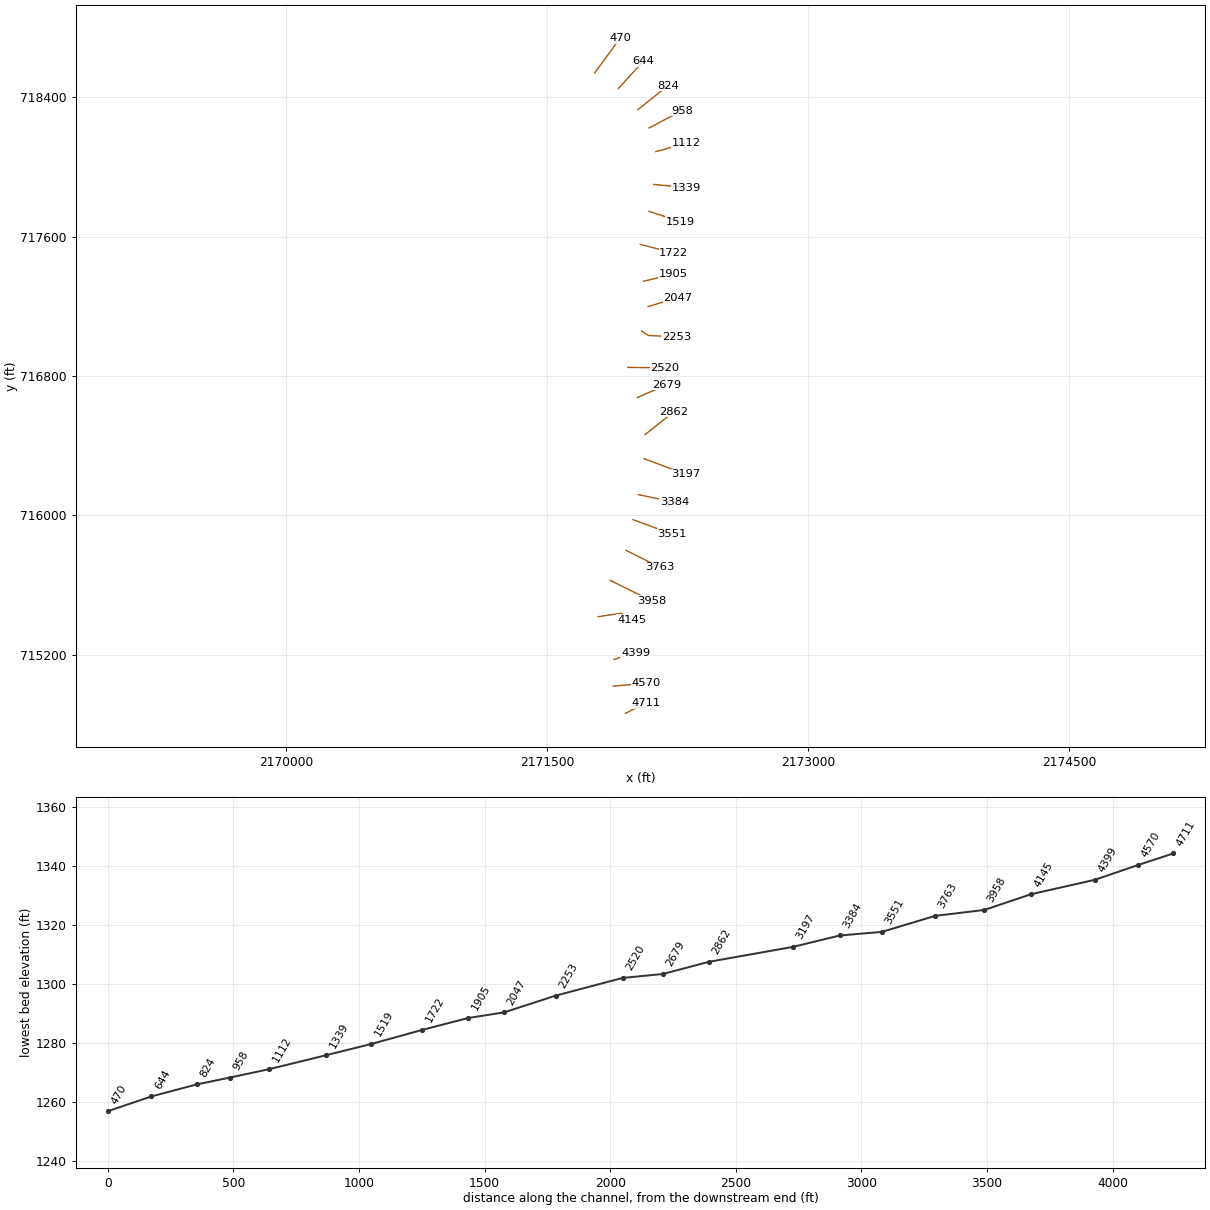
HEC-RAS study GLADYFK.prj: GLADYFK

--- GLADYFK.g01 (geometry) --- (continued)

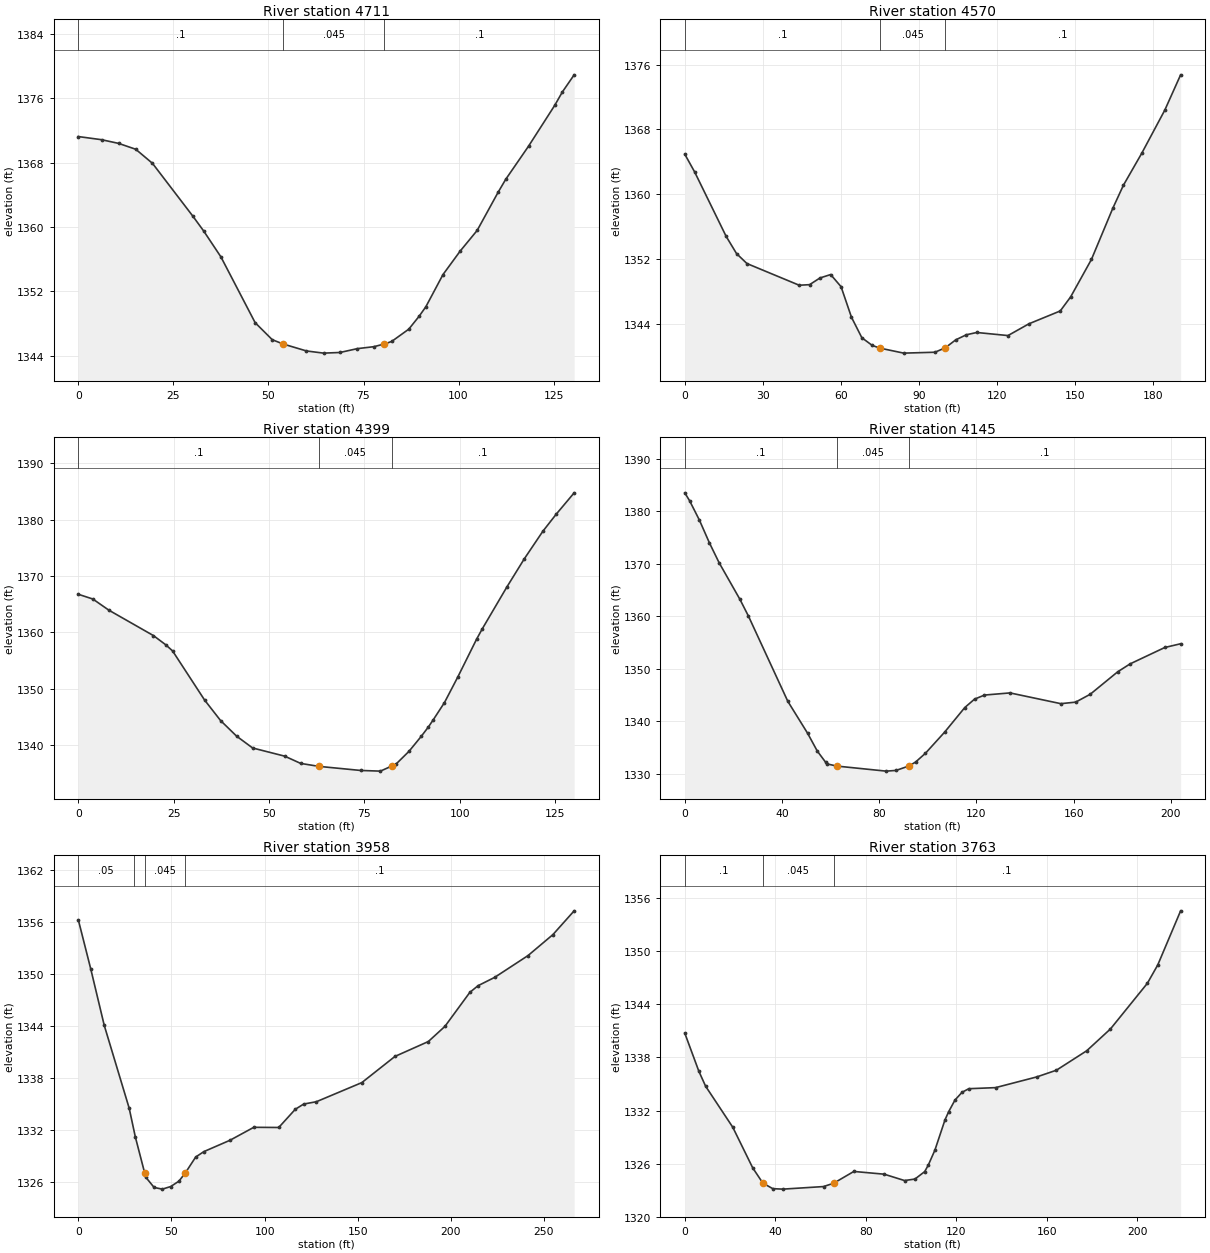
Type RM Length L Ch R = 1 ,4711    ,147.9,141.7,134.2
XS GIS Cut Line= 2
2171950.76517557714862.0601759772172066.91771738714921.382718789
#Sta/Elev= 30
       0 1371.26     6.1 1370.87    10.6 1370.41    15.1 1369.68    19.5 1367.93
    30.1 1361.37      33 1359.49    37.5 1356.29    46.5 1348.11      51 1345.99
    53.9 1345.45      60 1344.59    64.5 1344.32    68.8  1344.4    73.4 1344.88
    77.7 1345.12    80.51345.457    82.4 1345.77    86.9  1347.3    89.6 1348.89
    91.4 1350.09    95.9 1354.09   100.4    1357   104.9 1359.59   110.4 1364.33
   112.4 1365.94   118.4 1370.06   125.3 1375.15   127.3 1376.81   130.4 1378.94
#Mann= 3 ,-1,0
       0      .1       0    53.9    .045       0    80.5      .1       0
Bank Sta=53.9,80.5
XS Rating Curve= 0 ,0
Exp/Cntr(USF)=0,0
Exp/Cntr=0.3,0.1

Type RM Length L Ch R = 1 ,4570    ,166.9,170.9,173
XS GIS Cut Line= 2
2171880.34311552715018.4690500712172070.29463325715035.353629425
#Sta/Elev= 30
       0 1364.94     3.8 1362.74    15.9 1354.79    19.9 1352.66    23.9 1351.43
      44 1348.75      48 1348.82      52 1349.65    56.1 1350.07    60.1 1348.57
    64.1  1344.8    68.1 1342.26    72.1 1341.31   75.131340.972    84.2 1340.36
    96.2 1340.47   100.2 1341.02   104.2    1342   108.3 1342.63   112.3 1342.91
   124.3 1342.53   132.4 1343.99   144.4 1345.57   148.4 1347.31   156.4 1351.94
   164.6 1358.25   168.7 1361.11   175.7 1365.03   184.6 1370.38   190.7 1374.75
#Mann= 3 ,-1,0
       0      .1       0   75.13    .045       0   100.2      .1       0
Bank Sta=75.13,100.2
XS Rating Curve= 0 ,0
Exp/Cntr(USF)=0,0
Exp/Cntr=0.3,0.1

Type RM Length L Ch R = 1 ,4399    ,256.8,253.9,250.2
XS GIS Cut Line= 2
2171884.56426036715172.1187221892172008.66591861715210.953254702
#Sta/Elev= 30
       0 1366.77     3.8 1365.93       8 1363.95    19.7 1359.43    22.9 1357.81
    24.7 1356.72    33.1 1347.99    37.3 1344.34    41.5 1341.57    45.7 1339.47
    54.1 1338.02    58.3 1336.73   63.031336.207      74 1335.48    79.2 1335.36
   82.141336.251    83.4 1336.68    86.7 1338.88    89.9 1341.53    91.8 1343.22
    93.1 1344.52      96 1347.54    99.5 1352.09   104.4 1358.77   105.9 1360.62
   112.3    1368   116.9 1373.04   121.8 1377.97   125.3    1381     130 1384.79
#Mann= 3 ,-1,0
       0      .1       0   63.03    .045       0   82.14      .1       0
Bank Sta=63.03,82.14
XS Rating Curve= 0 ,0
Exp/Cntr(USF)=0,0
Exp/Cntr=0.3,0.1

Type RM Length L Ch R = 1 ,4145    ,195.6,186.6,173.4
XS GIS Cut Line= 3
2171794.20954314715417.4168553552171926.58701573 715436.84730353
2171985.68304347715398.856999985
#Sta/Elev= 30
       0 1383.52       2 1381.99       6 1378.33    10.1 1374.01    14.1 1370.21
    22.7  1363.2    26.2 1360.01    42.4 1343.76    50.5 1337.71    54.5  1334.3
    57.9 1332.19    58.6 1331.84    62.6 1331.43    82.8 1330.47    86.9  1330.6
   92.321331.468      95 1332.22      99 1333.87   106.9  1337.9   115.2 1342.59
   119.2 1344.19   123.3 1344.97   133.8 1345.38   154.7 1343.33   160.8 1343.62
   166.8 1345.12   178.1  1349.4   183.2 1350.91   197.5 1354.04     204 1354.75
#Mann= 3 ,-1,0
       0      .1       0    62.6    .045       0   92.32      .1       0
Bank Sta=62.6,92.32
XS Rating Curve= 0 ,0
Exp/Cntr(USF)=0,0
Exp/Cntr=0.3,0.1

Type RM Length L Ch R = 1 ,3958    ,194.9,195.5,195.1
XS GIS Cut Line= 2
2171863.70759151715625.7148729532172102.38467002715507.939720672
#Sta/Elev= 30
       0 1356.26     6.7 1350.56    13.9 1344.07    27.3 1334.48    30.6 1331.16
   35.59 1327.01    36.2  1326.5    40.7 1325.31    45.1 1325.12    49.6 1325.42
      54 1326.04    57.5 1327.01      63 1328.83    67.4 1329.46    81.4 1330.77
    94.2 1332.27   107.6 1332.25   116.5 1334.36     121 1334.96   127.8 1335.23
   152.2 1337.44     170 1340.47   187.9 1342.19   196.8 1343.94   210.2 1347.88
   214.6 1348.65   223.5 1349.61   241.4 1352.13   254.8 1354.56   266.2 1357.31
#Mann= 4 ,-1,0
       0     .05       0      30      .1       0   35.59    .045       0
    57.5      .1       0
Bank Sta=35.59,57.5
XS Rating Curve= 0 ,0
Exp/Cntr(USF)=0,0
Exp/Cntr=0.3,0.1

Type RM Length L Ch R = 1 ,3763    ,202.1,212,207.1
XS GIS Cut Line= 2
 2171953.3417782715798.7296984282172149.28627934715700.757447858
#Sta/Elev= 30
       0 1340.75     6.2 1336.45     9.2 1334.75    21.2 1330.11      30 1325.52
    34.5 1323.79    38.9 1323.16    43.4 1323.11    61.3  1323.4    65.8 1323.78
    74.7 1325.11    88.1  1324.8    97.1 1324.08   101.7 1324.25     106 1325.09
   107.6 1325.83   110.5 1327.51     115 1330.96   116.6 1331.87   119.4 1333.19
   122.5 1334.06   125.5 1334.47   137.3 1334.59   155.5  1335.8   164.2 1336.56
   177.6 1338.76   188.1 1341.23   204.4 1346.39     209 1348.47   219.1 1354.59
#Mann= 3 ,-1,0
       0      .1       0    34.5    .045       0    65.8      .1       0
Bank Sta=34.5,65.8
XS Rating Curve= 0 ,0
Exp/Cntr(USF)=0,0
Exp/Cntr=0.3,0.1

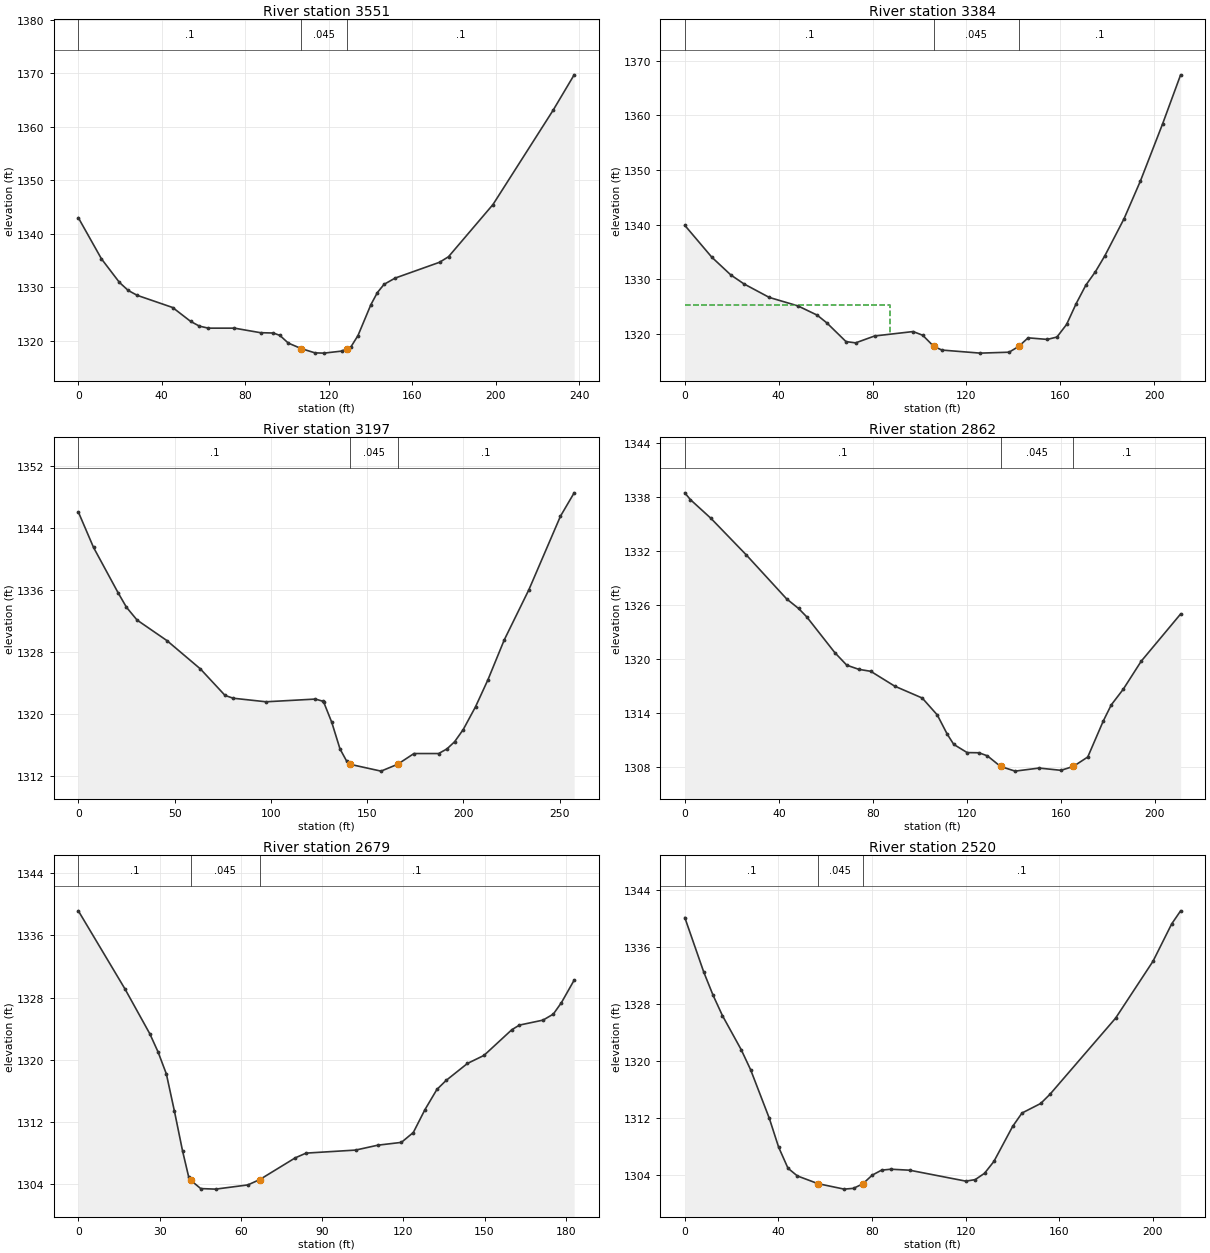
Type RM Length L Ch R = 1 ,3551    ,162.9,166.9,168.5
XS GIS Cut Line= 2
2171993.72250043715974.7571706072172216.64960164715892.698114949
#Sta/Elev= 30
       0 1342.99    11.1 1335.29    19.7 1330.89    23.9 1329.39    28.2 1328.48
    45.2  1326.2    53.8 1323.61      58 1322.72    62.3 1322.34    74.8 1322.34
    87.3 1321.49    93.5 1321.43    96.6 1320.98   100.6 1319.55  106.911318.503
   113.4 1317.72   117.7 1317.67   126.2 1318.05  128.921318.492   130.5 1318.76
     134 1320.95   140.2 1326.74   143.3 1328.99   146.5 1330.53   151.8  1331.7
   173.1 1334.66   177.4  1335.7   198.7 1345.46   227.5 1363.08   237.6 1369.71
#Mann= 3 ,-1,0
       0      .1       0  106.91    .045       0  128.92      .1       0
Bank Sta=106.91,128.92
XS Rating Curve= 0 ,0
Exp/Cntr(USF)=0,0
Exp/Cntr=0.3,0.1

Type RM Length L Ch R = 1 ,3384    ,190.5,187,184.6
XS GIS Cut Line= 2
2172024.96458628716118.3733352092172231.68849471716074.875675852
#Sta/Elev= 30
       0 1339.86    11.5 1334.03    19.6 1330.78    25.2 1329.14      36 1326.66
    48.2 1325.11    56.4 1323.42    60.5 1322.01    68.7 1318.57    72.8 1318.34
    80.9  1319.6    97.3 1320.41   101.4 1319.73   106.1 1317.69   109.6 1317.02
   125.9 1316.46   138.2 1316.63   142.3 1317.69   146.3 1319.26   154.5 1318.97
   158.6 1319.41   162.7 1321.71   166.8 1325.54   170.9  1328.9     175 1331.38
     179 1334.28   187.2 1341.08   194.2 1348.02   203.6 1358.42   211.3 1367.42
#Mann= 3 ,-1,0
       0      .1       0   106.1    .045       0   142.3      .1       0
#XS Ineff= 2 , 0
           87.46 1325.32
Permanent Ineff=
       F       F
Bank Sta=106.1,142.3
XS Rating Curve= 0 ,0
Exp/Cntr(USF)=0,0
Exp/Cntr=0.3,0.1

Type RM Length L Ch R = 1 ,3197    ,318.5,334.8,356
XS GIS Cut Line= 2
2172056.75862441716324.9414458742172298.14901314716235.360310114
#Sta/Elev= 30
       0 1346.03     7.9 1341.45    20.7 1335.58      25 1333.73    30.5 1332.08
      46 1329.43    63.4 1325.77    76.2 1322.35    80.4 1321.99    97.5 1321.53
   123.1 1321.88   126.9 1321.61   127.4 1321.51   131.6 1318.89   135.9 1315.44
   139.4 1313.85  141.31 1313.45   157.2 1312.58   165.8 1313.46   174.3 1314.85
   187.1 1314.85   191.4 1315.44   195.4 1316.37   199.9 1317.95   206.3  1320.9
   212.7 1324.36   221.2 1329.52     234    1336   250.4 1345.49   257.5  1348.5
#Mann= 3 ,-1,0
       0      .1       0  141.31    .045       0   165.8      .1       0
Bank Sta=141.31,165.8
XS Rating Curve= 0 ,0
Exp/Cntr(USF)=0,0
Exp/Cntr=0.3,0.1

Type RM Length L Ch R = 1 ,2862    ,186.6,182.7,177.2
XS GIS Cut Line= 2
2172062.32436311716462.230805985 2172227.2022805716593.677256252
#Sta/Elev= 30
       0 1338.43     2.4 1337.67    11.1  1335.6    26.2 1331.52    43.3 1326.65
    48.4 1325.58    51.8 1324.67    63.8 1320.68    68.9 1319.28      74 1318.82
    79.1  1318.6    89.3 1316.95     101 1315.63   107.4 1313.75   111.6 1311.63
   114.4 1310.48   120.1 1309.57   125.1 1309.55   128.7 1309.21   134.3 1308.03
   140.5 1307.51   150.7 1307.85     160  1307.6  165.261308.031   171.4 1309.08
     178 1313.08   181.4 1314.87   186.5 1316.61   194.1 1319.71   210.9 1324.97
#Mann= 3 ,-1,0
       0      .1       0   134.3    .045       0  165.26      .1       0
Bank Sta=134.3,165.26
XS Rating Curve= 0 ,0
Exp/Cntr(USF)=0,0
Exp/Cntr=0.3,0.1

Type RM Length L Ch R = 1 ,2679    ,164.5,159.5,151.2
XS GIS Cut Line= 2
2172018.75068354716675.8998306082172186.67002554716748.857889543
#Sta/Elev= 30
       0 1339.16    17.3 1329.07    26.4 1323.35    29.4 1321.05    32.5  1318.2
    35.5 1313.38    38.5 1308.27    40.8 1304.88   41.511304.516    45.2 1303.45
    50.7 1303.38    62.6 1303.92      67 1304.61    80.1  1307.4    84.1 1308.01
   102.4  1308.4   110.6 1309.03   119.3 1309.39   123.7 1310.66     128  1313.6
   132.4 1316.19   135.8 1317.35   143.7 1319.54   149.8 1320.57   160.1 1323.88
   162.9 1324.47   171.6 1325.11   175.4 1325.88   178.4 1327.36   183.1 1330.25
#Mann= 3 ,-1,0
       0      .1       0   41.51    .045       0      67      .1       0
Bank Sta=41.51,67
XS Rating Curve= 0 ,0
Exp/Cntr(USF)=0,0
Exp/Cntr=0.3,0.1

Type RM Length L Ch R = 1 ,2520    ,261.1,267.3,253.5
XS GIS Cut Line= 2
2171964.07127926716849.055596113 2172175.9970695716846.739467258
#Sta/Elev= 30
       0 1340.11     8.1 1332.47    12.1 1329.21    16.1 1326.36    24.1  1321.6
    28.1 1318.81    36.1    1312    40.1 1307.94    44.1 1304.99    48.1 1303.91
    56.9 1302.83    68.1 1302.06    72.1 1302.17    76.1 1302.81    80.1 1304.02
    84.1 1304.72    88.1 1304.85    96.1 1304.71   120.1 1303.18   124.1 1303.39
   128.1 1304.28   132.1 1305.94   140.1 1310.84   144.1 1312.72   152.1 1314.06
   156.1 1315.36   184.1 1326.01   200.1 1333.99   208.1 1339.23   211.9 1341.05
#Mann= 3 ,-1,0
       0      .1       0    56.9    .045       0    76.1      .1       0
Bank Sta=56.9,76.1
XS Rating Curve= 0 ,0
Exp/Cntr(USF)=0,0
Exp/Cntr=0.3,0.1

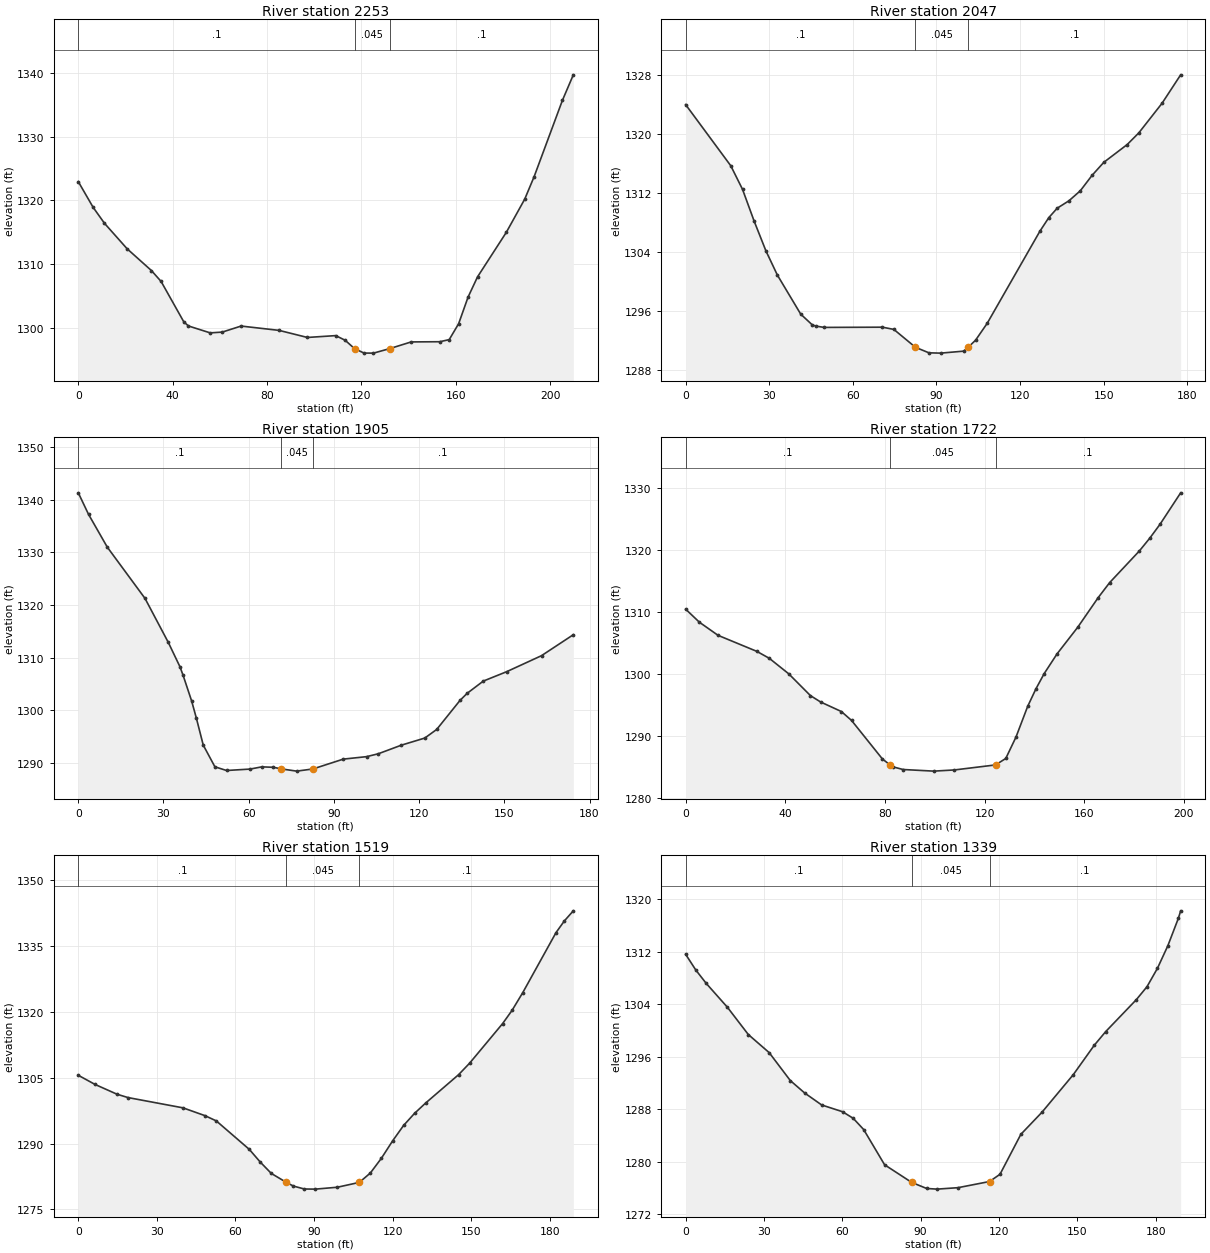
Type RM Length L Ch R = 1 ,2253    ,201,205.7,211.4
XS GIS Cut Line= 3
2172042.92670856 717058.277919922172081.85123588717032.504200498
2172244.69743184 717023.90539077
#Sta/Elev= 30
       0 1322.95     6.3 1318.91    11.1 1316.41    20.7 1312.41      31 1308.99
    35.1 1307.28    44.7 1300.95    46.7 1300.29    55.9 1299.21      61 1299.33
      69 1300.28    85.1  1299.6    97.1 1298.49   109.1 1298.78   113.1 1298.05
   117.1 1296.73   121.1 1296.04   125.1 1296.03     132 1296.74   141.1 1297.79
   153.2 1297.82   157.2 1298.15   161.2 1300.65   165.2 1304.83   169.2    1308
   181.4 1314.99   189.2  1320.2   193.2 1323.74   205.2 1335.73   209.8 1339.72
#Mann= 3 ,-1,0
       0      .1       0   117.1    .045       0     132      .1       0
Bank Sta=117.1,132
XS Rating Curve= 0 ,0
Exp/Cntr(USF)=0,0
Exp/Cntr=0.3,0.1

Type RM Length L Ch R = 1 ,2047    ,143.1,142.4,141.5
XS GIS Cut Line= 2
2172080.66433438717198.1218313072172250.52657959717249.819036371
#Sta/Elev= 30
       0 1323.97    16.2 1315.69    20.4 1312.51    24.6 1308.18    28.8 1304.18
    32.9 1300.91    41.3 1295.61    45.5 1294.14    46.9 1293.99    49.7 1293.82
    70.6 1293.85    74.7 1293.55   82.461291.126    87.3 1290.38    91.5 1290.34
    99.8 1290.61   101.4 1291.15     104 1292.08   108.2 1294.38   127.1 1306.84
   130.3 1308.68   133.3 1309.95   137.5 1310.95   141.6 1312.31   145.8 1314.39
     150 1316.15   158.4 1318.56   162.6 1320.15   170.9 1324.14   177.6    1328
#Mann= 3 ,-1,0
       0      .1       0   82.46    .045       0   101.4      .1       0
Bank Sta=82.46,101.4
XS Rating Curve= 0 ,0
Exp/Cntr(USF)=0,0
Exp/Cntr=0.3,0.1

Type RM Length L Ch R = 1 ,1905    ,190,182.3,173.6
XS GIS Cut Line= 2
2172053.28570755717343.7799382132172223.06953327717383.177290038
#Sta/Elev= 30
       0  1341.3     3.6 1337.22    10.2 1330.99    23.5 1321.24    31.7 1312.88
    35.8 1308.26    36.9 1306.64    39.9 1301.78    41.6 1298.45      44 1293.38
    48.1 1289.26    52.2 1288.56    60.5 1288.83    64.6 1289.25    68.7 1289.17
    71.5 1288.86    76.9 1288.44   82.581288.847    93.3 1290.72   101.5 1291.19
   105.6 1291.73   113.8 1293.38     122 1294.72   126.2 1296.36   134.4 1301.87
   136.9 1303.21   142.6 1305.54   150.8 1307.32   163.1 1310.37   174.3 1314.35
#Mann= 3 ,-1,0
       0      .1       0    71.5    .045       0   82.58      .1       0
Bank Sta=71.5,82.58
XS Rating Curve= 0 ,0
Exp/Cntr(USF)=0,0
Exp/Cntr=0.3,0.1

Type RM Length L Ch R = 1 ,1722    ,202.9,203.5,200.7
XS GIS Cut Line= 2
2172035.57481564717555.299442394 2172228.2084488717506.679451916
#Sta/Elev= 30
       0 1310.52     5.5 1308.42      13  1306.3    28.6 1303.71    33.6 1302.59
    41.4 1300.09    50.1 1296.58    54.2 1295.55    62.5 1294.02    66.6 1292.58
      79 1286.36   82.051285.413    83.1 1285.11    87.3 1284.67    99.6 1284.41
   107.9  1284.6   124.4 1285.41   128.5 1286.45   132.6  1289.9   137.3 1294.86
   140.6 1297.67   143.9 1300.12   149.1 1303.32   157.4 1307.61   165.6 1312.38
   170.2  1314.8   182.1 1319.89   186.3 1321.96   190.4 1324.19   198.7 1329.27
#Mann= 3 ,-1,0
       0      .1       0   82.05    .045       0   124.4      .1       0
Bank Sta=82.05,124.4
XS Rating Curve= 0 ,0
Exp/Cntr(USF)=0,0
Exp/Cntr=0.3,0.1

Type RM Length L Ch R = 1 ,1519    ,175.2,179.3,183.6
XS GIS Cut Line= 2
2172086.10510867717745.0360569482172265.81444056717686.568979791
#Sta/Elev= 30
       0 1305.52     6.4 1303.44    14.8 1301.21      19 1300.45      40 1298.11
    48.4 1296.33    52.7 1295.14    65.3 1288.66    69.5 1285.76    73.7 1283.19
   79.42 1281.16    82.1 1280.32    86.3 1279.65    90.5 1279.62    98.9 1280.05
   107.3 1281.15   111.5 1283.28   115.7 1286.62     120 1290.59   124.2 1294.11
   128.4 1296.87   132.6  1299.2   145.2 1305.66   149.4 1308.27     162 1317.28
   165.6 1320.28   169.7 1324.33   182.4 1337.99   185.6 1340.66     189 1342.94
#Mann= 3 ,-1,0
       0      .1       0   79.42    .045       0   107.3      .1       0
Bank Sta=79.42,107.3
XS Rating Curve= 0 ,0
Exp/Cntr(USF)=0,0
Exp/Cntr=0.3,0.1

Type RM Length L Ch R = 1 ,1339    ,220.5,227,233.9
XS GIS Cut Line= 2
2172112.29421688717899.916990113 2172301.0300449717882.137528054
#Sta/Elev= 30
       0 1311.58     3.9 1309.18     7.9 1307.14      16 1303.51      24 1299.36
      32  1296.6    40.1 1292.34    45.6 1290.45    52.1 1288.63    60.1  1287.6
    64.2 1286.59    68.2 1284.88    76.2 1279.52   86.571276.837    92.3 1275.91
    96.3 1275.81   104.3 1276.03   116.4 1276.97   120.4 1278.07   128.4 1284.16
   136.5 1287.53   148.5 1293.26   156.5 1297.72   160.9 1299.81   172.6 1304.66
   176.7 1306.64   180.7 1309.44   184.7 1312.89   188.7 1317.04   189.6  1318.2
#Mann= 3 ,-1,0
       0      .1       0   86.57    .045       0   116.4      .1       0
Bank Sta=86.57,116.4
XS Rating Curve= 0 ,0
Exp/Cntr(USF)=0,0
Exp/Cntr=0.3,0.1

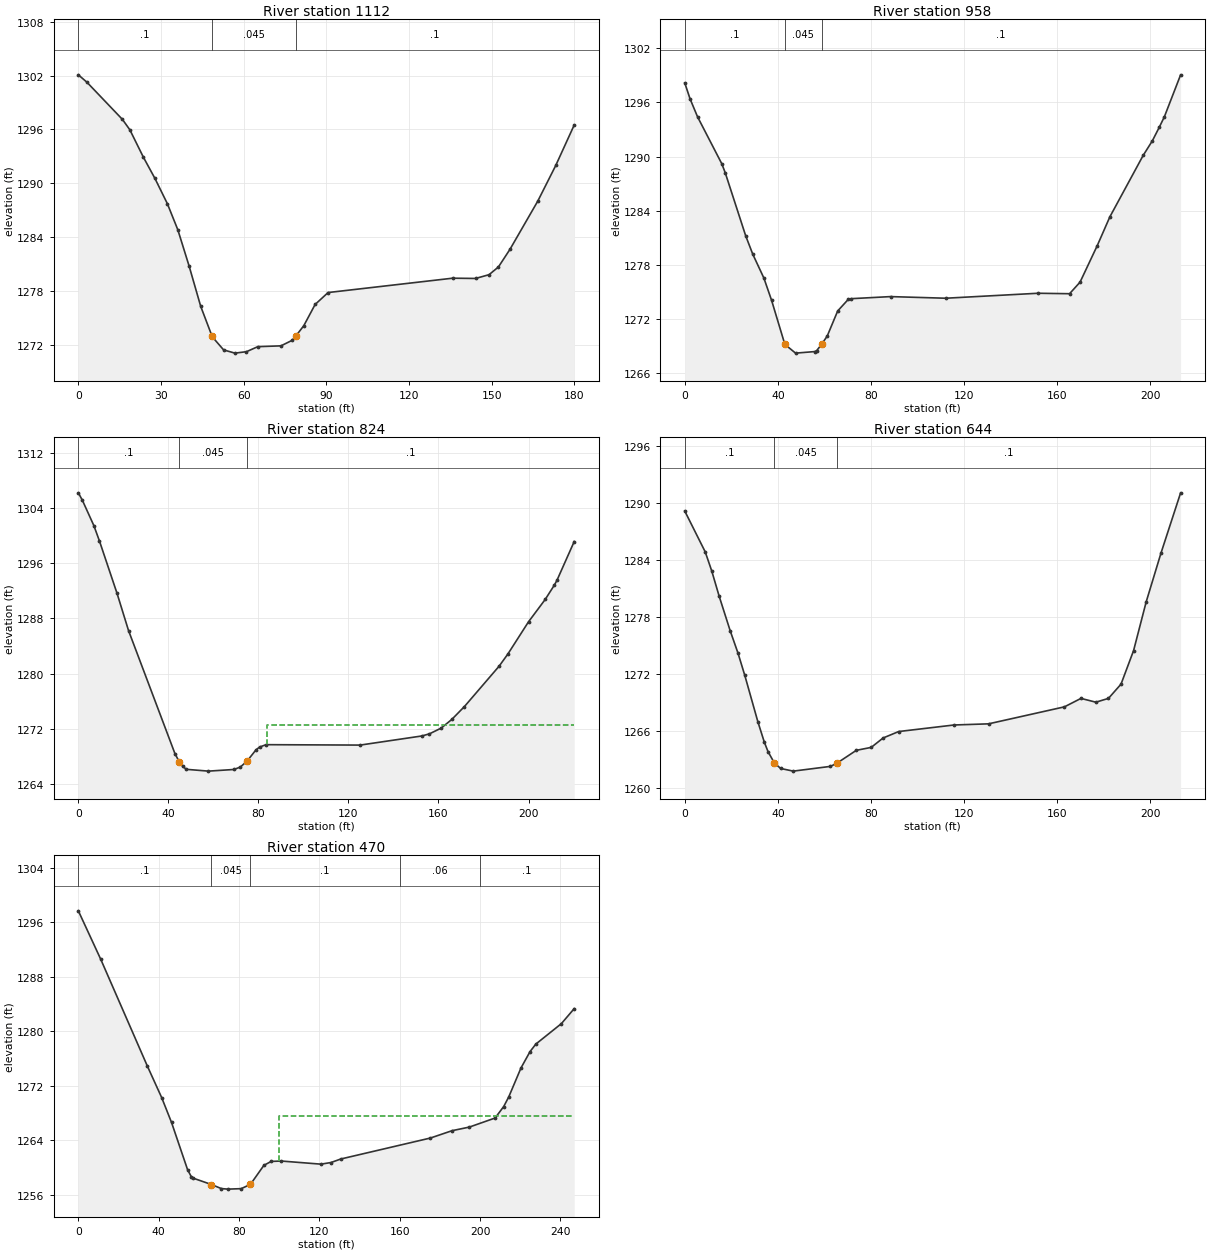
Type RM Length L Ch R = 1 ,1112    ,151.6,154.9,158.5
XS GIS Cut Line= 2
2172125.45033833718088.1342716192172298.68612249718136.761860157
#Sta/Elev= 30
       0 1302.08     3.1 1301.26      16 1297.11    18.7 1295.95    23.6  1292.9
    27.8 1290.53    32.3 1287.72    36.1 1284.81    40.2 1280.76    44.4 1276.28
    48.5 1272.96    48.5 1272.92    52.7 1271.43    56.8 1271.07      61 1271.23
    65.1 1271.79    73.5 1271.88    77.6  1272.5   78.881272.965    81.8 1274.13
    85.9 1276.49    90.6 1277.82   135.8 1279.42   144.1 1279.39     149 1279.81
   152.4 1280.67   156.6 1282.64   166.7 1288.02   173.2 1291.98   179.9 1296.49
#Mann= 3 ,-1,0
       0      .1       0    48.5    .045       0   78.88      .1       0
Bank Sta=48.5,78.88
XS Rating Curve= 0 ,0
Exp/Cntr(USF)=0,0
Exp/Cntr=0.3,0.1

Type RM Length L Ch R = 1 ,958     ,131,133.9,139.1
XS GIS Cut Line= 2
2172086.12535266718223.7540129292172274.38841245718323.373031115
#Sta/Elev= 30
       0 1298.17     2.3 1296.39     5.5 1294.41    15.9 1289.22    17.4 1288.21
    26.2 1281.22    29.2 1279.21      34 1276.55    37.3 1274.09      43 1269.21
    47.6 1268.24    55.8 1268.41    56.6 1268.49    58.8 1269.22    61.2 1270.13
    65.7 1272.91    70.2 1274.18    71.5 1274.27    88.4  1274.5   112.1 1274.32
   151.7 1274.87   165.3 1274.82   169.8  1276.1   177.2 1280.15   182.6 1283.33
   196.9 1290.13   200.9 1291.77   203.8 1293.24     206  1294.4     213 1299.06
#Mann= 3 ,-1,0
       0      .1       0      43    .045       0    58.8      .1       0
Bank Sta=43,58.8
XS Rating Curve= 0 ,0
Exp/Cntr(USF)=0,0
Exp/Cntr=0.3,0.1

Type RM Length L Ch R = 1 ,824     ,175.9,179.9,180.2
XS GIS Cut Line= 2
2172022.80818009718329.2826338892172194.18666052718467.736184589
#Sta/Elev= 30
       0 1306.17     1.8 1305.09     6.9 1301.42     9.4 1299.18    17.2 1291.61
    22.3 1286.23    42.9 1268.43    44.81267.246    46.4 1266.55      48 1266.14
    57.8 1265.88    69.2 1266.12      72 1266.48    74.9 1267.31    78.9 1268.95
    80.5 1269.36    83.4 1269.71   125.2 1269.65   152.6 1270.97     156 1271.28
   161.2 1272.11   165.9 1273.36   171.5 1275.22   186.9 1281.06   190.8 1282.82
     200  1287.5   207.4 1290.73   211.4 1292.77   212.6 1293.48   220.3 1299.12
#Mann= 3 ,-1,0
       0      .1       0    44.8    .045       0    74.9      .1       0
#XS Ineff= 2 , 0
                           83.88          1272.5
Permanent Ineff=
       F       F
Bank Sta=44.8,74.9
XS Rating Curve= 0 ,0
Exp/Cntr(USF)=0,0
Exp/Cntr=0.3,0.1

Type RM Length L Ch R = 1 ,644     ,171.2,174,174.9
XS GIS Cut Line= 2
  2171910.192907718450.777389066 2172053.7962544718608.057245745
#Sta/Elev= 30
       0 1289.21     8.8  1284.9    11.6 1282.89    14.8 1280.22    19.5 1276.61
    22.9 1274.22    25.8 1271.89    31.4 1267.02    34.2 1264.85    35.8 1263.85
    38.5 1262.67    41.2 1262.09    46.6 1261.81    62.6 1262.31    65.4 1262.65
    73.7    1264    80.1 1264.31    85.2  1265.3    91.9 1265.98   115.7 1266.67
   130.5 1266.79   163.1 1268.58   170.2 1269.47   176.6 1269.07     182 1269.47
   187.4 1270.97   192.8 1274.51   198.2 1279.63   204.6  1284.8     213 1291.12
#Mann= 3 ,-1,0
       0      .1       0    38.5    .045       0    65.4      .1       0
Bank Sta=38.5,65.4
XS Rating Curve= 0 ,0
Exp/Cntr(USF)=0,0
Exp/Cntr=0.3,0.1

Type RM Length L Ch R = 1 ,470     ,150.4,169.9,179.1
XS GIS Cut Line= 2
2171773.54466294 718539.731444522171919.46078081718738.918526058
#Sta/Elev= 30
       0 1297.69    11.2 1290.54    34.4 1274.85    41.5 1270.24    46.4 1266.59
    54.4 1259.64    56.3 1258.59    57.3 1258.39   66.24 1257.47    71.2 1256.87
    74.5 1256.79    81.1 1256.86    85.7 1257.49    92.4 1260.29      96 1260.86
     101 1260.92   120.8 1260.46   125.8  1260.7   130.7 1261.22   175.3  1264.3
   186.1 1265.38   194.7 1265.91   207.5 1267.24   211.8 1268.93   214.3 1270.34
   220.4  1274.6   224.9    1277   227.8 1278.11   240.5 1281.11   246.9 1283.32
#Mann= 5 ,-1,0
       0      .1       0   66.24    .045       0    85.7      .1       0
     160     .06       0     200      .1       0
#XS Ineff= 2 , 0
                           99.83         1267.55
Permanent Ineff=
       F       F
Bank Sta=66.24,85.7
XS Rating Curve= 0 ,0
Exp/Cntr(USF)=0,0
Exp/Cntr=0.3,0.1