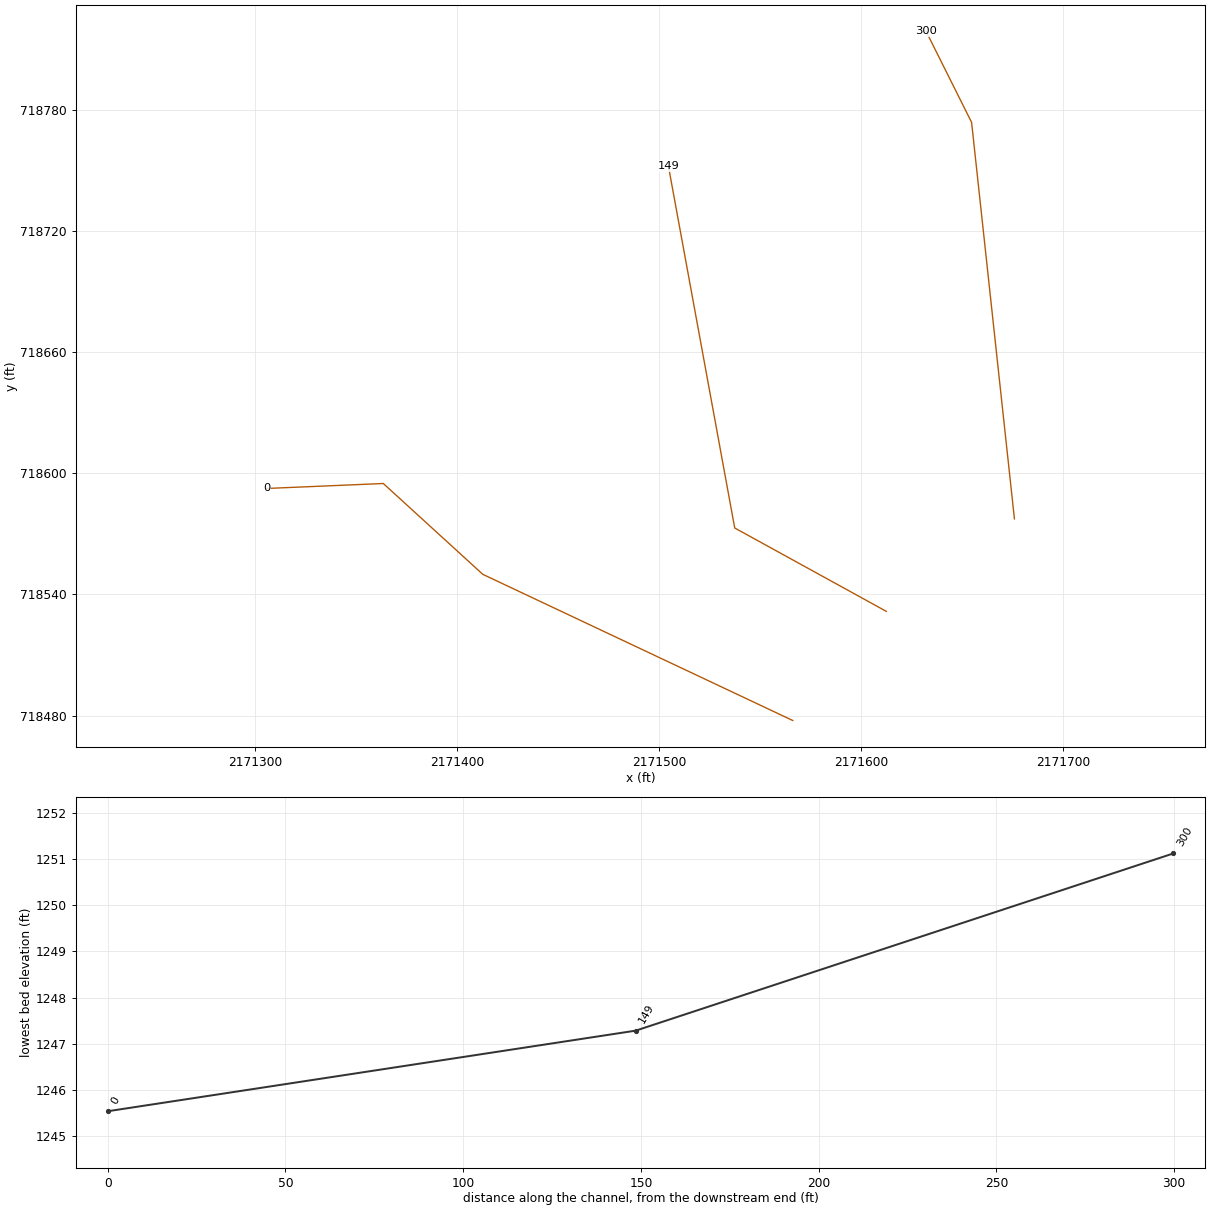
HEC-RAS study GLADYFK.prj: GLADYFK

--- GLADYFK.g01 (geometry) --- (continued)

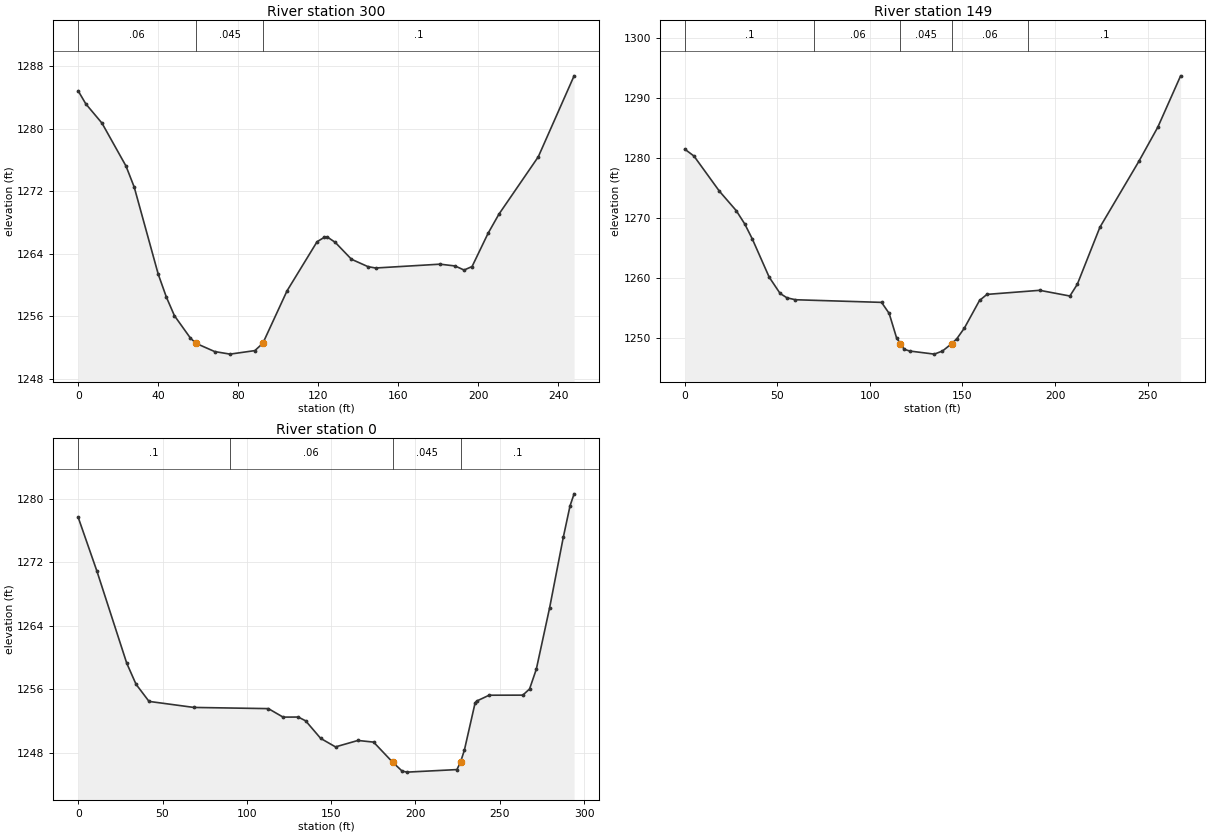
Type RM Length L Ch R = 1 ,300     ,142.4,151.3,148.1
XS GIS Cut Line= 3
2171675.94753259718577.3738770922171654.74894322718773.631785209
2171632.18270291718818.764265821
#Sta/Elev= 30
       0 1284.81     3.8 1283.15    11.9 1280.68    23.9 1275.19      28  1272.5
      40 1261.36    44.1 1258.41    48.1 1256.05    56.1 1253.18   58.961252.503
    68.2 1251.46    75.9 1251.13    88.3 1251.58    92.3 1252.52   104.4 1259.23
   119.4 1265.51   123.1 1266.09   124.5 1266.12   128.5 1265.43   136.6 1263.27
   144.9 1262.32   148.7 1262.15   180.9 1262.64   188.4 1262.41   192.9 1261.89
   196.9 1262.34   204.9 1266.59   210.3 1269.03     230 1276.38   247.9 1286.74
#Mann= 3 ,-1,0
       0     .06       0   58.96    .045       0    92.3      .1       0
Bank Sta=58.96,92.3
XS Rating Curve= 0 ,0
Exp/Cntr(USF)=0,0
Exp/Cntr=0.3,0.1

Type RM Length L Ch R = 1 ,149     ,148.5,148.5,148.5
XS GIS Cut Line= 3
2171612.52999057718531.5735175632171537.48741567718572.846933761
2171504.65628915718752.011081346
#Sta/Elev= 30
       0 1281.43       5 1280.27    18.7 1274.43    27.8 1271.19    32.4 1268.97
    36.5 1266.46    45.6 1260.11    51.5 1257.39    55.2 1256.66    59.8 1256.34
   106.3  1255.9   110.4 1254.06   114.4 1249.99  116.491249.018   118.5  1248.1
   121.4  1247.8   134.8 1247.28   139.2  1247.8   144.2 1249.03     147 1249.87
     151 1251.61   159.2 1256.22   163.2 1257.23   191.7 1257.91     208 1256.96
     212 1258.91   224.2 1268.41   245.2 1279.37   255.5  1285.1   267.8 1293.64
#Mann= 5 ,-1,0
       0      .1       0      70     .06       0  116.49    .045       0
   144.2     .06       0  185.64      .1       0
Bank Sta=116.49,144.2
XS Rating Curve= 0 ,0
Exp/Cntr(USF)=0,0
Exp/Cntr=0.3,0.1

Type RM Length L Ch R = 1 ,0       ,178.3,178.3,178.3
XS GIS Cut Line= 4
2171566.20489151718477.5492067392171412.77892616718549.903093645
2171363.52356582718594.8669219482171305.84117553718592.412572116
#Sta/Elev= 30
       0 1277.62    11.1 1270.85    28.8 1259.24    34.3  1256.6      42 1254.44
    68.6 1253.68   112.8 1253.53   121.5 1252.46   130.5 1252.47   134.9 1251.99
   143.8 1249.78   152.6 1248.71   165.9 1249.52   175.2 1249.31   186.4  1246.8
   192.1 1245.66     195 1245.53   224.6 1245.85  226.731246.791     229 1248.27
   235.4 1254.26   236.3 1254.48   243.7 1255.22   263.7 1255.23   267.7 1256.01
   271.7  1258.5   279.6 1266.25   287.7 1275.12   291.7 1279.08   294.1 1280.59
#Mann= 4 ,-1,0
       0      .1       0      90     .06       0   186.4    .045       0
  226.73      .1       0
Bank Sta=186.4,226.73
XS Rating Curve= 0 ,0
Exp/Cntr=0.3,0.1
LCMann Table=0

Chan Stop Cuts=-1
Use User Specified Reach Order=0
Composite Channel Slope=5